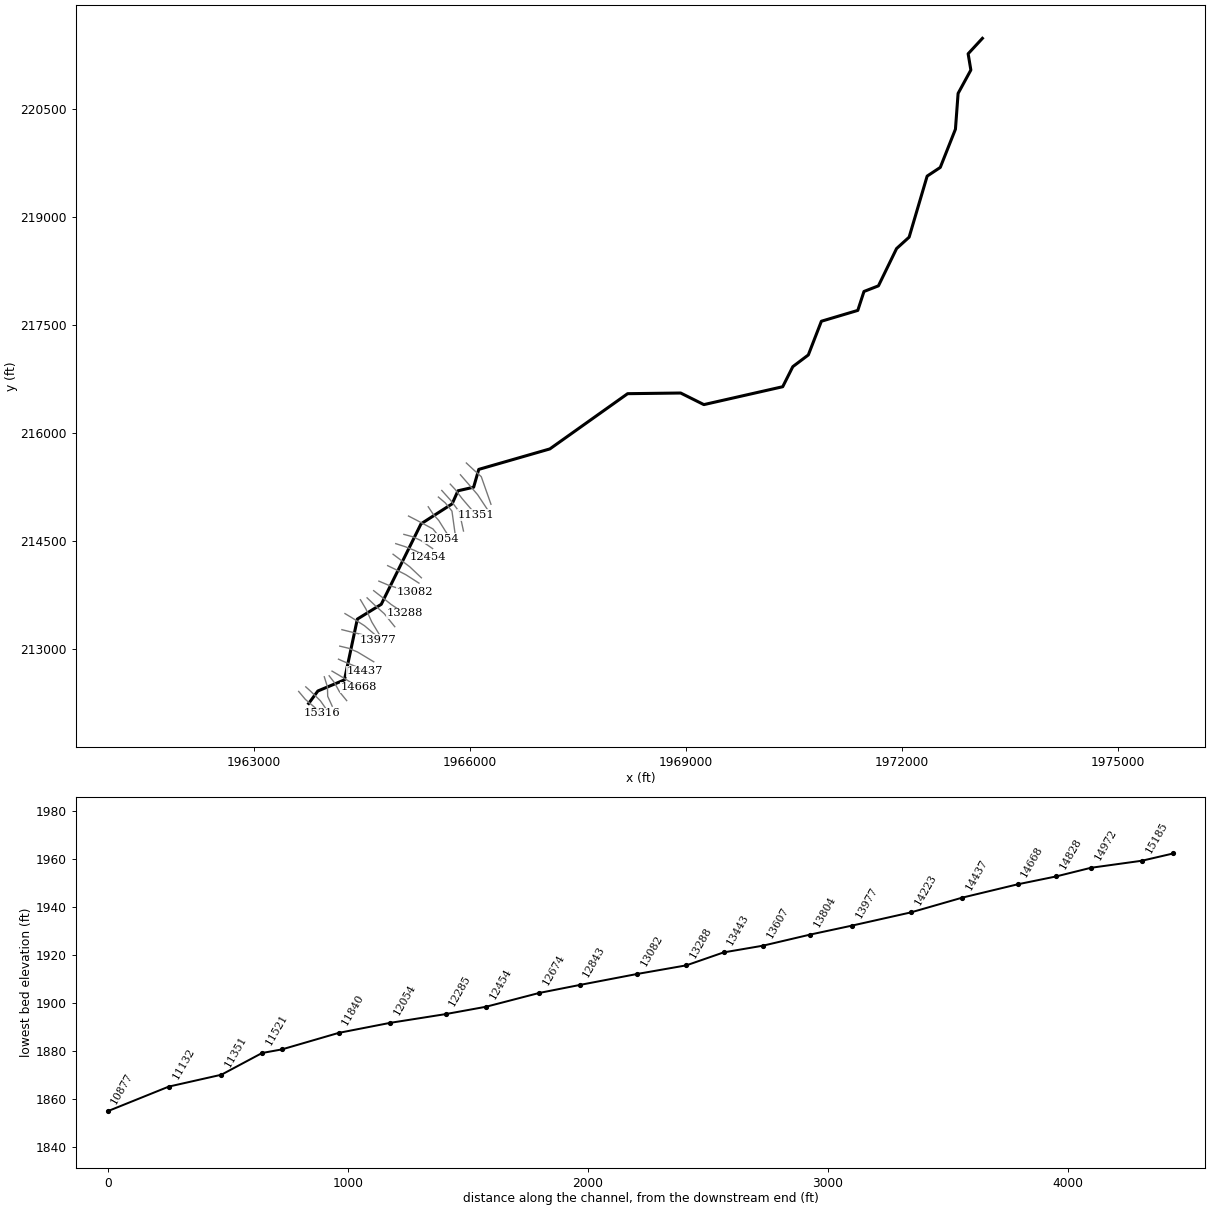
--- SUCKCK.prj (project) ---

Proj Title=SUCKCK
Current Plan=p01
Default Exp/Contr=0,0
English Units
Geom File=g01
Flow File=f01
Plan File=p01
Background Map Layer=QC
BEGIN DESCRIPTION:
Stream Name: Suck Creek
Flood Zone: Approximate
Summers County, West Virginia
HEC-RAS Version: 5.0.7
Hydrology Method:
Regression.
Model Notes:
END DESCRIPTION:
DSS Export Rating Curves= 0
DSS Export Rating Curve Sorted= 0
DSS Export Volume Flow Curves= 0
DXF OffsetX= 0
DXF OffsetY= 0
DXF ScaleX= 0
DXF ScaleY= 0

--- SUCKCK.p01 (plan) ---

Plan Title=Floodplain
Program Version=5.07
Short Identifier=Floodplain
Geom File=g01
Flow File=f01
Subcritical Flow
K Sum by GR= 0
Std Step Tol= 0.01
Critical Tol= 0.01
Num of Std Step Trials= 20
Max Error Tol= 0.3
Flow Tol Ratio= 0.001
Split Flow NTrial= 30
Split Flow Tol= 0.02
Split Flow Ratio= 0.02
Log Output Level= 0
Friction Slope Method= 1
Unsteady Friction Slope Method= 2
Unsteady Bridges Friction Slope Method= 1
Parabolic Critical Depth
Global Vel Dist= 0 , 0 , 0
Global Log Level= 0
CheckData=True
Encroach Param=-1 ,0,0, 0
Mapping Interval=1HOUR
Computation Time Step Use Courant=        0
Computation Time Step Use Time Series=    0
Computation Time Step Count To Double=0
Computation Time Step Max Doubling=0
Computation Time Step Max Halving=0
Computation Time Step Residence Courant=0
Run HTab= 0
Run UNet= 0
Run Sediment= 0
Run PostProcess= 0
Run WQNet= 0
Run RASMapper= 0
UNET Theta= 0
UNET Theta Warmup= 0
UNET ZTol= 0
UNET ZSATol= 0
UNET MxIter= 0
UNET Max Iter WO Improvement= 0
UNET MaxInSteps= 0
UNET DtIC= 0
UNET DtMin= 0
UNET MaxCRTS= 0
UNET WFStab= 0
UNET SFStab= 0
UNET WFX= 1
UNET SFX= 1
UNET 1D Methodology=Finite Difference
UNET DSS MLevel= 1
UNET Pardiso=0
UNET DZMax Abort= 0
UNET Use Existing IB Tables= 0
UNET Froude Reduction=False
UNET Froude Limit= 0
UNET Froude Power= 0
UNET D1 Cores= 0
UNET D2 Coriolis=0
UNET D2 Cores= 0
UNET D2 Theta= 1
UNET D2 Theta Warmup= 1
UNET D2 Z Tol= 0.01
UNET D2 Volume Tol= 0.01
UNET D2 Max Iterations= 20
UNET D2 Equation= 0
UNET D2 RampUpFraction=0.1
UNET D2 TimeSlices= 1
UNET D2 BCVolumeCheck=0
UNET D1D2 MaxIter= 0
UNET D1D2 ZTol=0.01
UNET D1D2 QTol=0.1
UNET D1D2 MinQTol=1
Write IC File= 0
Write IC File at Fixed DateTime=0
Write IC File at Sim End=0
Echo Input=False
Echo Parameters=False
Echo Output=False
Write Detailed= 0
HDF Write Warmup=0
HDF Write Time Slices=0
HDF Flush=0
HDF Face Node Velocities=0
HDF Compression= 1
HDF Chunk Size= 1
HDF Spatial Parts= 1
HDF Use Max Rows=0
HDF Fixed Rows= 1
Calibration Method= 0
Calibration Iterations= 20
Calibration Max Change=0.05
Calibration Tolerance=0.2
Calibration Maximum=1.5
Calibration Minimum=0.5
Calibration Optimization Method= 1
WQ AD Non Conservative
WQ ULTIMATE=-1
WQ Max Comp Step=1HOUR
WQ Output Interval=15MIN
WQ Output Selected Increments= 0
WQ Output face flow=0
WQ Output face velocity=0
WQ Output face area=0
WQ Output face dispersion=0
WQ Output cell volume=0
WQ Output cell surface area=0
WQ Output cell continuity=0
WQ Output cumulative cell continuity=0
WQ Output face conc=0
WQ Output face dconc_dx=0
WQ Output face courant=0
WQ Output face peclet=0
WQ Output face adv mass=0
WQ Output face disp mass=0
WQ Output cell mass=0
WQ Output cell source sink temp=0
WQ Output nsm pathways=0
WQ Output nsm derived pathways=0
WQ Output MaxMinRange=-1
WQ Daily Max Min Mean=-1
WQ Daily Range=0
WQ Daily Time=0
WQ Create Restart=0
WQ Fixed Restart=0
WQ System Summary=0
WQ Write To DSS=0
WQ Use Fixed Temperature=0
Sorting and Armoring Iterations= 10
XS Update Threshold= 0.02
Bed Roughness Predictor= 0
Hydraulics Update Threshold= 0.02
Energy Slope Method= 1
Volume Change Method= 1
Sediment Retention Method= 0
XS Weighting Method= 0
Number of US Weighted Cross Sections= 1
Number of DS Weighted Cross Sections= 1
Upstream XS Weight=0
Main XS Weight=1
Downstream XS Weight=0
Number of DS XS's Weighted with US Boundary= 1
Upstream Boundary Weight= 1
Weight of XSs Associated with US Boundary= 0
Number of US XS's Weighted with DS Boundary= 1
Downstream Boundary Weight= 0.5
Weight of XSs Associated with DS Boundary= 0.5
Percentile Method= 0
Sediment Output Level= 3
Mass or Volume Output= 0
Output Increment Type= 1
Profile and TS Output Increment= 1
XS Output Flag= 0
XS Output Increment= 10
Write Gradation File= 0
Read Gradation Hotstart= 0
Write HDF5 File= 1
Write Binary Output= 1
Write DSS Sediment File= 0
SV Curve= 0
Specific Gage Flag= 0

--- SUCKCK.f01 (steady flow) ---

Flow Title=Flows
Program Version=5.07
Number of Profiles= 6
Profile Names=01pct,10pct,04pct,02pct,0_2pct,01plus
River Rch & RM=SUCKCK,Main            ,15316
     804     430     569     683    1116    1189
River Rch & RM=SUCKCK,Main            ,9856
    1117     605     795     951    1540    1651
River Rch & RM=SUCKCK,Main            ,8690
    1247     679     890    1063    1717    1845
River Rch & RM=SUCKCK,Main            ,7461
    1388     759     993    1185    1907    2053
Boundary for River Rch & Prof#=SUCKCK,Main            , 1
Up Type= 0
Dn Type= 3
Dn Slope=0.00709
Boundary for River Rch & Prof#=SUCKCK,Main            , 2
Up Type= 0
Dn Type= 3
Dn Slope=0.00709
Boundary for River Rch & Prof#=SUCKCK,Main            , 3
Up Type= 0
Dn Type= 3
Dn Slope=0.00709
Boundary for River Rch & Prof#=SUCKCK,Main            , 4
Up Type= 0
Dn Type= 3
Dn Slope=0.00709
Boundary for River Rch & Prof#=SUCKCK,Main            , 5
Up Type= 0
Dn Type= 3
Dn Slope=0.00709
Boundary for River Rch & Prof#=SUCKCK,Main            , 6
Up Type= 0
Dn Type= 3
Dn Slope=0.00709
DSS Import GetInterval= 0
DSS Import GetPeak= 0
DSS Import FillOption= 0

--- SUCKCK.g01 (geometry) ---

Geom Title=Geometry
Program Version=5.07

River Reach=SUCKCK          ,Main
Reach XY= 30
     1963760.921      212246.747      1963888.96      212420.358
     1964257.883      212574.438      1964436.92      213418.622
     1964769.016      213623.862     1965321.251      214741.322
     1965753.109        215019.1      1965834.49      215200.306
1966051.79037742 215250.17699355     1966123.118      215497.615
     1967110.531      215781.903     1968190.363      216548.968
     1968926.551      216558.126     1969249.203      216397.138
     1970344.038      216645.619     1970484.321      216924.364
     1970699.554      217086.653     1970881.048      217554.978
     1971386.592      217705.398      1971472.51      217968.318
     1971673.248      218046.444     1971924.984      218564.022
     1972099.442      218722.434     1972349.671      219570.241
     1972531.963      219690.9011972742.50982099220221.461029282
     1972779.535      220718.806     1972956.573      221043.452
     1972918.908        221269.1     1973117.169      221483.488

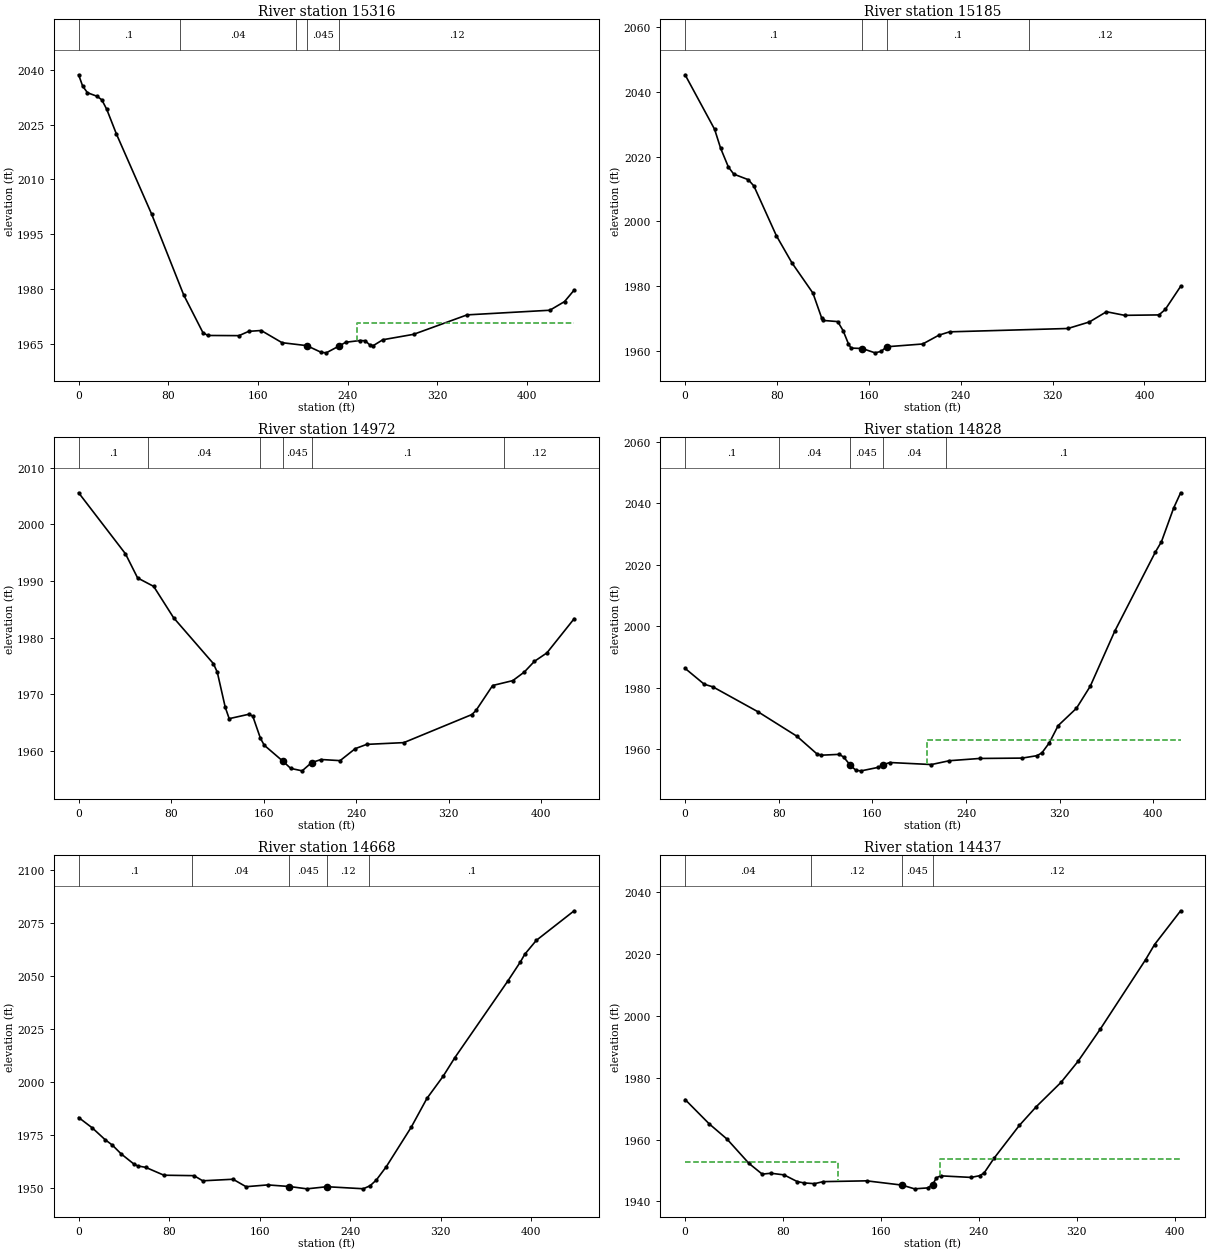
Type RM Length L Ch R = 1 ,15316   ,131.1,131.1,131.1
XS GIS Cut Line= 4
1963622.16183078212414.0281613391963714.54913404212304.162179091
1963846.88770356 212190.550765631963940.52348389212109.399756014
#Sta/Elev= 30
       0 2038.68     3.6 2035.56     7.9 2033.76    16.5 2032.78    20.7  2031.8
    25.1  2029.2    33.7 2022.45      65 2000.58    93.7 1978.36   110.8 1968.06
   115.1 1967.26     143 1967.21   151.7 1968.39   162.8 1968.62   181.4 1965.28
  203.471964.474   216.3 1962.64   220.8  1962.5   232.6 1964.43   238.2  1965.4
   251.1 1965.88   255.5 1965.81   259.8 1964.63   262.8 1964.49   271.3 1966.09
   298.7 1967.57   346.4  1972.9   420.2 1974.17   433.3 1976.54   441.9  1979.7
#Mann= 5 ,-1 , 0
       0      .1       0      90     .04       0  193.55      .1       0
  203.47    .045       0   232.6     .12       0
#XS Ineff= 2 , 0
                          248.57          1970.6
Permanent Ineff=
       F       F
Bank Sta=203.47,232.6
XS Rating Curve= 0 ,0
Exp/Cntr(USF)=0,0
Exp/Cntr=0.3,0.1

Type RM Length L Ch R = 1 ,15185   ,228.5,212.8,197.5
XS GIS Cut Line= 4
1963720.79151939212477.7004919611963786.96080416212417.773592552
 1963923.0448049212285.4350230261964010.43819987212160.587315925
#Sta/Elev= 30
       0 2045.23    25.7 2028.41    30.9  2022.6    37.7 2016.77    42.4 2014.58
      55 2012.87    59.9 2010.93    79.5 1995.57      93 1987.23   111.3 1977.89
     119 1970.12   120.5 1969.44   132.9 1969.09   137.6 1966.29   142.2 1962.25
   144.5 1960.92   154.21960.786   165.4 1959.45   170.8 1959.91   175.4 1961.32
   206.9 1962.18     221  1964.9   230.3 1965.93   333.3 1966.96   352.1 1968.98
   366.9 1972.13   382.7 1971.02   412.6 1971.15   418.1 1972.83   431.5 1979.96
#Mann= 4 ,-1 , 0
       0      .1       0   154.2    .045       0   175.4      .1       0
  299.09     .12       0
Bank Sta=154.2,175.4
XS Rating Curve= 0 ,0
Exp/Cntr(USF)=0,0
Exp/Cntr=0.3,0.1

Type RM Length L Ch R = 1 ,14972   ,131.5,144.6,151.2
XS GIS Cut Line= 4
1963977.97779602212617.529923913 1964021.6744935212477.700491961
1964025.41992472212346.6103995051964087.84377827212209.277921695
#Sta/Elev= 30
       0 2005.57    40.5  1994.8      51 1990.54    64.9 1989.05    82.1 1983.52
   116.5 1975.43   119.9 1973.91   126.8  1967.7   130.2 1965.71   147.3 1966.49
   150.6 1966.14   157.2 1962.25   160.5 1961.02   176.8 1958.17   183.4 1956.93
   193.3  1956.5   201.41957.947   209.7  1958.5   226.1  1958.3   239.2 1960.42
   249.1 1961.17   281.2 1961.48     340 1966.43   343.6 1967.15     358 1971.56
   375.4 1972.42   385.3 1973.92   394.1 1975.82   404.9 1977.31   428.5 1983.35
#Mann= 6 ,-1 , 0
       0      .1       0      60     .04       0   156.5      .1       0
   176.8    .045       0   201.4      .1       0  367.64     .12       0
Bank Sta=176.8,201.4
XS Rating Curve= 0 ,0
Exp/Cntr(USF)=0,0
Exp/Cntr=0.3,0.1

Type RM Length L Ch R = 1 ,14828   ,144.4,160,170.3
XS GIS Cut Line= 4
1964045.39555785212631.2631716941964120.30418211212533.881960156
1964188.97042102212409.034253055 1964288.8485867212286.683500097
#Sta/Elev= 30
       0 1986.26    16.4 1981.08    23.7 1980.25    62.4  1972.1    95.5 1964.17
   112.6 1958.42   116.2 1957.99   131.8 1958.27   135.5 1957.35  140.86 1954.85
     146 1953.03   150.5  1952.9   165.2 1954.05  168.721954.847     175 1955.61
   210.4 1954.95   225.8  1956.2   251.6 1956.93   287.9 1957.05   300.6 1957.84
   304.8 1958.76   311.1 1962.01   318.7 1967.64   334.3 1973.27   346.1 1980.45
     367 1998.35   401.7 2024.12   406.9 2027.49   417.3 2038.44   423.3 2043.43
#Mann= 5 ,-1 , 0
       0      .1       0      80     .04       0  140.86    .045       0
  168.72     .04       0  222.86      .1       0
#XS Ineff= 2 , 0
                           206.3         1963.05
Permanent Ineff=
       F       F
Bank Sta=140.86,168.72
XS Rating Curve= 0 ,0
Exp/Cntr(USF)=0,0
Exp/Cntr=0.3,0.1

Type RM Length L Ch R = 1 ,14668   ,224.1,231.3,233.9
XS GIS Cut Line= 4
1964085.34682413212696.1839793861964177.73412738212642.499465333
1964350.02396318212537.6273913691964459.88994543212468.961152464
#Sta/Elev= 30
       0 1983.23    12.1 1978.33    23.3 1972.84    29.9 1970.19    37.5 1966.13
    48.8 1961.33    52.1 1960.44    59.3 1959.74    75.4 1956.04     102 1955.83
   109.7 1953.41   136.5 1954.14     148 1950.63   167.2 1951.47   186.4 1950.72
   201.8 1949.62   219.5 1950.62   251.7 1949.66   257.7 1951.08   263.2 1953.78
   272.1 1960.14     294 1978.62   307.9 1992.22   322.2 2002.63   332.5 2011.36
   379.3 2047.44   390.6 2056.59   394.4 2060.14   404.6 2066.69   438.1 2080.65
#Mann= 5 ,-1 , 0
       0      .1       0     100     .04       0   186.4    .045       0
   219.5     .12       0  256.85      .1       0
Bank Sta=186.4,219.5
XS Rating Curve= 0 ,0
Exp/Cntr(USF)=0,0
Exp/Cntr=0.3,0.1

Type RM Length L Ch R = 1 ,14437   ,213,213.1,213.2
XS GIS Cut Line= 4
1964175.23717324 212862.23142983 1964232.6671185212836.013411339
1964418.69020208212758.6078329371964543.53790918212694.935502315
#Sta/Elev= 30
       0 1972.96    19.7 1965.08    34.2 1960.17    52.2 1952.27      63 1948.81
    70.1  1949.1    80.8 1948.57    91.5 1946.42    96.9 1945.98   105.7 1945.72
   112.8 1946.38   148.3 1946.64   177.2 1945.26   187.4 1944.05   198.1 1944.35
   202.3 1945.45   205.2  1947.6   208.7 1948.26   233.6 1947.75   240.7 1948.31
   244.3 1949.21   252.4 1953.97     273 1964.56   286.9 1970.66   307.1 1978.52
   320.9 1985.28   339.3 1995.84   376.1 2018.19   383.5 2023.13   404.8 2034.06
#Mann= 4 ,-1 , 0
       0     .04       0  103.13     .12       0   177.2    .045       0
   202.3     .12       0
#XS Ineff= 2 , 0
          124.64 1952.58  208.45         1953.69
Permanent Ineff=
       F       F
Bank Sta=177.2,202.3
XS Rating Curve= 0 ,0
Exp/Cntr(USF)=0,0
Exp/Cntr=0.3,0.1

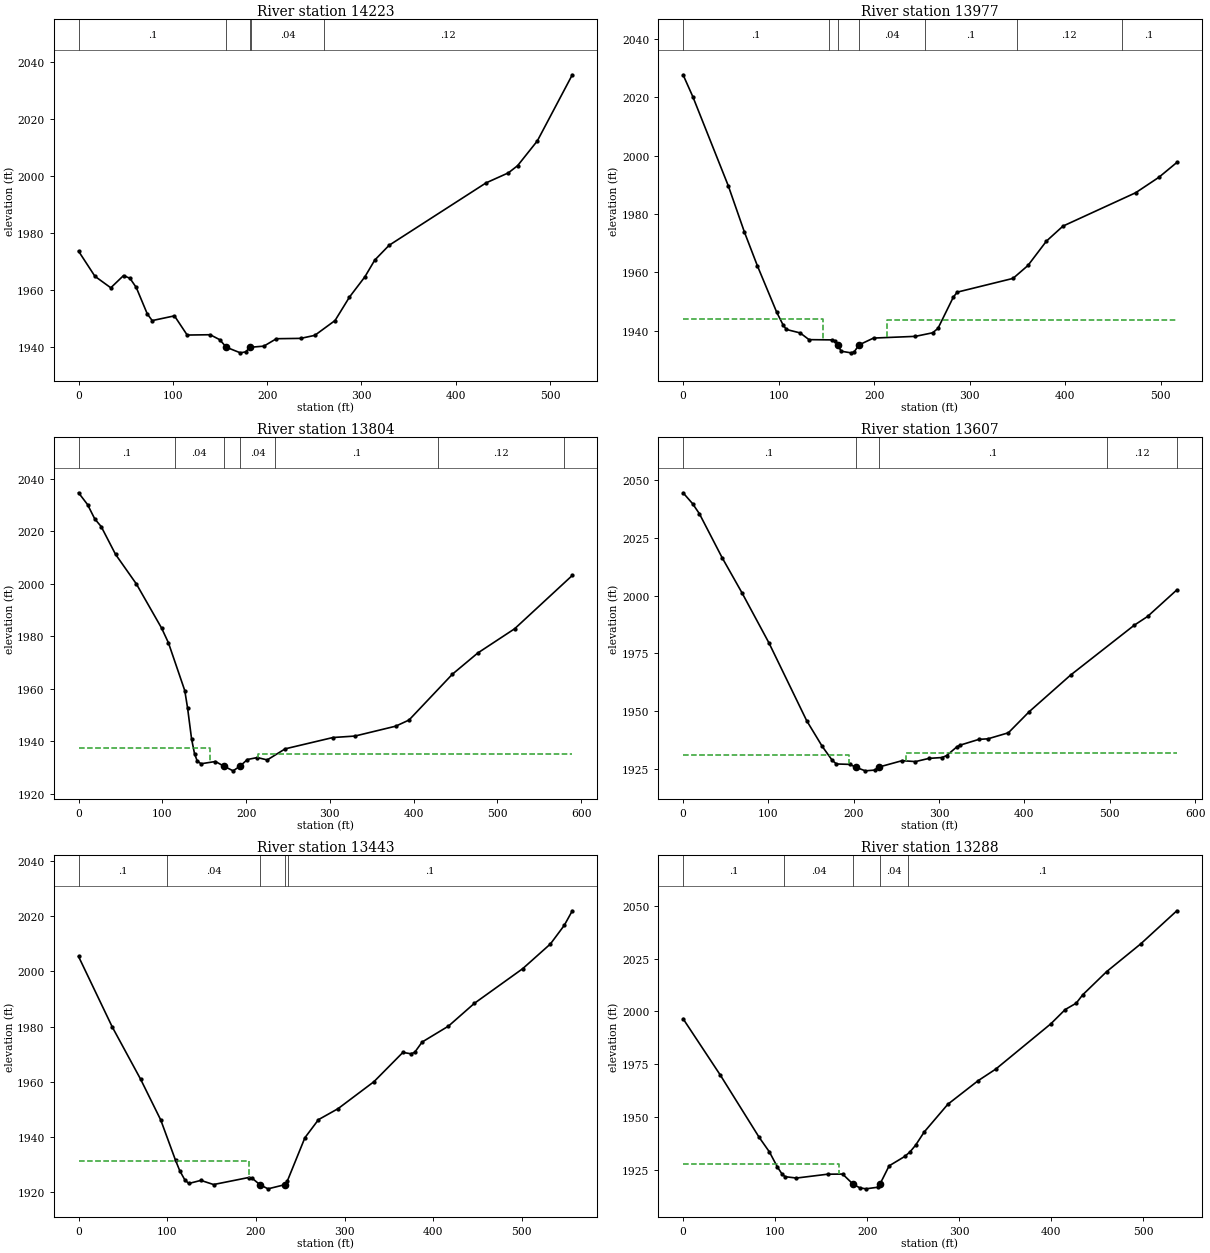
Type RM Length L Ch R = 1 ,14223   ,241.4,246.1,248.1
XS GIS Cut Line= 4
1964192.71585223213043.2606051261964312.56965105213014.545632493
1964438.66583522 212962.109595511964664.64018507212826.025594771
#Sta/Elev= 30
       0 1973.64    17.4  1964.8    34.2 1960.77    47.7 1965.06    54.5 1964.11
    61.2 1960.88    72.9 1951.59    78.1 1949.25   101.7 1950.91   115.2 1944.17
   139.6 1944.28   149.6 1942.56   156.8 1939.87   171.6 1937.92   177.2 1938.27
  181.931939.872   196.5 1940.27   209.8 1942.88   235.6    1943   250.5 1944.06
     272 1949.27   287.3 1957.51   303.7 1964.65   314.1  1970.5   329.3 1975.69
   432.1 1997.61   455.8 2001.14   465.6 2003.67   486.5 2012.36   523.6 2035.59
#Mann= 5 ,-1 , 0
       0      .1       0   156.8    .045       0  181.93      .1       0
  183.25     .04       0  259.81     .12       0
Bank Sta=156.8,181.93
XS Rating Curve= 0 ,0
Exp/Cntr(USF)=0,0
Exp/Cntr=0.3,0.1

Type RM Length L Ch R = 1 ,13977   ,180.9,173.2,168.7
XS GIS Cut Line= 4
1964222.67930194 213271.731909121964332.54528418213244.265413557
1964503.58664291213203.065670214 1964719.5731762213130.654000096
#Sta/Elev= 30
       0 2027.67    10.2 2020.18    47.4 1989.59    64.3 1973.72    77.8 1962.23
    98.1 1946.27   104.9 1941.84   108.3 1940.39   122.6 1939.21   131.9 1936.91
   155.5 1936.83   158.9 1936.55  161.791935.105   165.6 1932.94   175.8 1932.39
   179.1 1932.68  184.221935.103   199.4 1937.45   243.3 1938.04   261.3 1939.26
   266.9 1940.77     283 1951.49   287.1 1953.19   345.5  1957.9   361.1 1962.32
   380.5 1970.69   397.8 1975.82   473.9 1987.25   498.2 1992.54     517 1997.62
#Mann= 7 ,-1 , 0
       0      .1       0  153.25     .04       0  161.79    .045       0
  184.22     .04       0  253.25      .1       0  349.18     .12       0
  459.18      .1       0
#XS Ineff= 2 , 0
          146.13 1943.84  214.04         1943.58
Permanent Ineff=
       F       F
Bank Sta=161.79,184.22
XS Rating Curve= 0 ,0
Exp/Cntr(USF)=0,0
Exp/Cntr=0.3,0.1

Type RM Length L Ch R = 1 ,13804   ,210.2,197.2,186.9
XS GIS Cut Line= 4
1964265.12752235213495.2093048291964355.01787146213441.524790776
1964536.04704676213326.6649002441964742.04576347213151.878110303
#Sta/Elev= 30
       0 2034.71    10.7 2030.24    19.4 2024.72      27 2021.84    44.2 2011.21
    69.1  1999.9    99.2 1983.06   107.3 1977.48   126.8 1959.25   130.2 1952.47
   134.9 1940.84   138.4 1935.24   141.6 1932.44   146.2 1931.37   163.4 1932.23
  173.231930.483   184.5 1928.67  192.811930.484   201.5 1932.99   213.4 1933.74
   225.2 1932.83   246.6 1937.06   303.7 1941.38   329.8 1941.93   378.5  1945.7
   394.4 1948.04   446.2 1965.53   476.4 1973.59   520.5 1982.86   589.3 2003.19
#Mann= 7 ,-1 , 0
       0      .1       0   114.7     .04       0  173.23    .045       0
  192.81     .04       0   234.7      .1       0  429.09     .12       0
  579.09      .1       0
#XS Ineff= 2 , 0
          157.31 1937.22  213.93         1935.23
Permanent Ineff=
       F       F
Bank Sta=173.23,192.81
XS Rating Curve= 0 ,0
Exp/Cntr(USF)=0,0
Exp/Cntr=0.3,0.1

Type RM Length L Ch R = 1 ,13607   ,156.3,164.1,176.1
XS GIS Cut Line= 4
1964479.86557856213687.4747737641964556.02267989213558.881635451
1964637.17368951213379.1009372261964757.02748833213180.593082936
#Sta/Elev= 30
       0 2044.61    11.1 2039.92    19.1 2035.55    45.7 2016.52      69 2001.26
   100.6 1979.54   144.9 1945.74   163.1 1934.63   174.8 1928.59   179.7 1927.01
   195.5 1926.83   202.1 1925.64   213.5 1924.03   224.4 1924.35   229.3 1925.65
   256.7 1928.44   272.3 1928.04   288.3 1929.44   303.5  1929.8   308.7 1930.62
   321.1 1934.51   325.1 1935.22   346.7 1937.68   357.3 1937.92   381.2 1940.53
   405.7 1949.71     454 1965.52   528.7 1987.18   544.3 1990.97   578.6 2002.49
#Mann= 5 ,-1 , 0
       0      .1       0   202.1    .045       0   229.3      .1       0
   496.7     .12       0  578.58      .1       0
#XS Ineff= 2 , 0
          195.01 1930.99  261.01         1931.84
Permanent Ineff=
       F       F
Bank Sta=202.1,229.3
XS Rating Curve= 0 ,0
Exp/Cntr(USF)=0,0
Exp/Cntr=0.3,0.1

Type RM Length L Ch R = 1 ,13443   ,153.9,155,156
XS GIS Cut Line= 4
1964572.25288182213713.6927922551964699.59754306213592.590516368
1964809.46352531213495.2093048291964956.78381969213312.931652463
#Sta/Elev= 30
       0 2005.41      38 1979.89      70 1960.94    92.7 1946.18   109.4 1931.55
   114.2 1927.75   119.8 1924.51   124.3 1923.16     138 1924.28   152.3 1922.78
   191.7 1925.31   196.1 1924.98  204.631922.704   213.7 1921.22  232.391922.705
   235.5 1924.06   255.3 1939.74   270.6 1946.29   292.6 1950.25   333.2 1960.05
   365.8 1970.65   374.8 1970.16   379.1 1970.66   387.5 1974.41   417.2 1980.18
   446.5 1988.45   500.9 2000.98   532.2 2009.95   547.8 2016.68   556.9 2021.97
#Mann= 5 ,-1 , 0
       0      .1       0     100     .04       0  204.63    .045       0
  232.39     .04       0  235.73      .1       0
#XS Ineff= 2 , 0
          191.76 1931.46
Permanent Ineff=
       F       F
Bank Sta=204.63,232.39
XS Rating Curve= 0 ,0
Exp/Cntr(USF)=0,0
Exp/Cntr=0.3,0.1

Type RM Length L Ch R = 1 ,13288   ,199.1,205.5,216.7
XS GIS Cut Line= 4
  1964663.391708213813.5709579361964785.74246096213718.686700539
1964906.84473685213621.3054890011965095.36477457  213496.4577819
#Sta/Elev= 30
       0 1996.57    40.2 1969.99    82.6 1940.31    93.8 1933.34   102.5 1926.15
   107.8 1922.68   110.8  1921.6   123.2 1920.95   156.9 1922.77   173.3 1922.84
  184.631918.051   191.9 1916.32   198.6 1915.83   211.2 1916.58  213.851918.052
   223.8 1926.74   240.7 1931.18   246.5 1933.36   252.6 1936.56   261.9  1942.8
   287.6 1955.98   320.4 1967.13   339.7 1972.68   399.4 1994.13   415.1 2000.93
     427 2003.93   434.1 2007.92   460.1 2018.93   497.1 2032.09   536.3 2047.79
#Mann= 5 ,-1 , 0
       0      .1       0     110     .04       0  184.63    .045       0
  213.85     .04       0  244.83      .1       0
#XS Ineff= 2 , 0
          169.34 1927.55
Permanent Ineff=
       F       F
Bank Sta=184.63,213.85
XS Rating Curve= 0 ,0
Exp/Cntr(USF)=0,0
Exp/Cntr=0.3,0.1

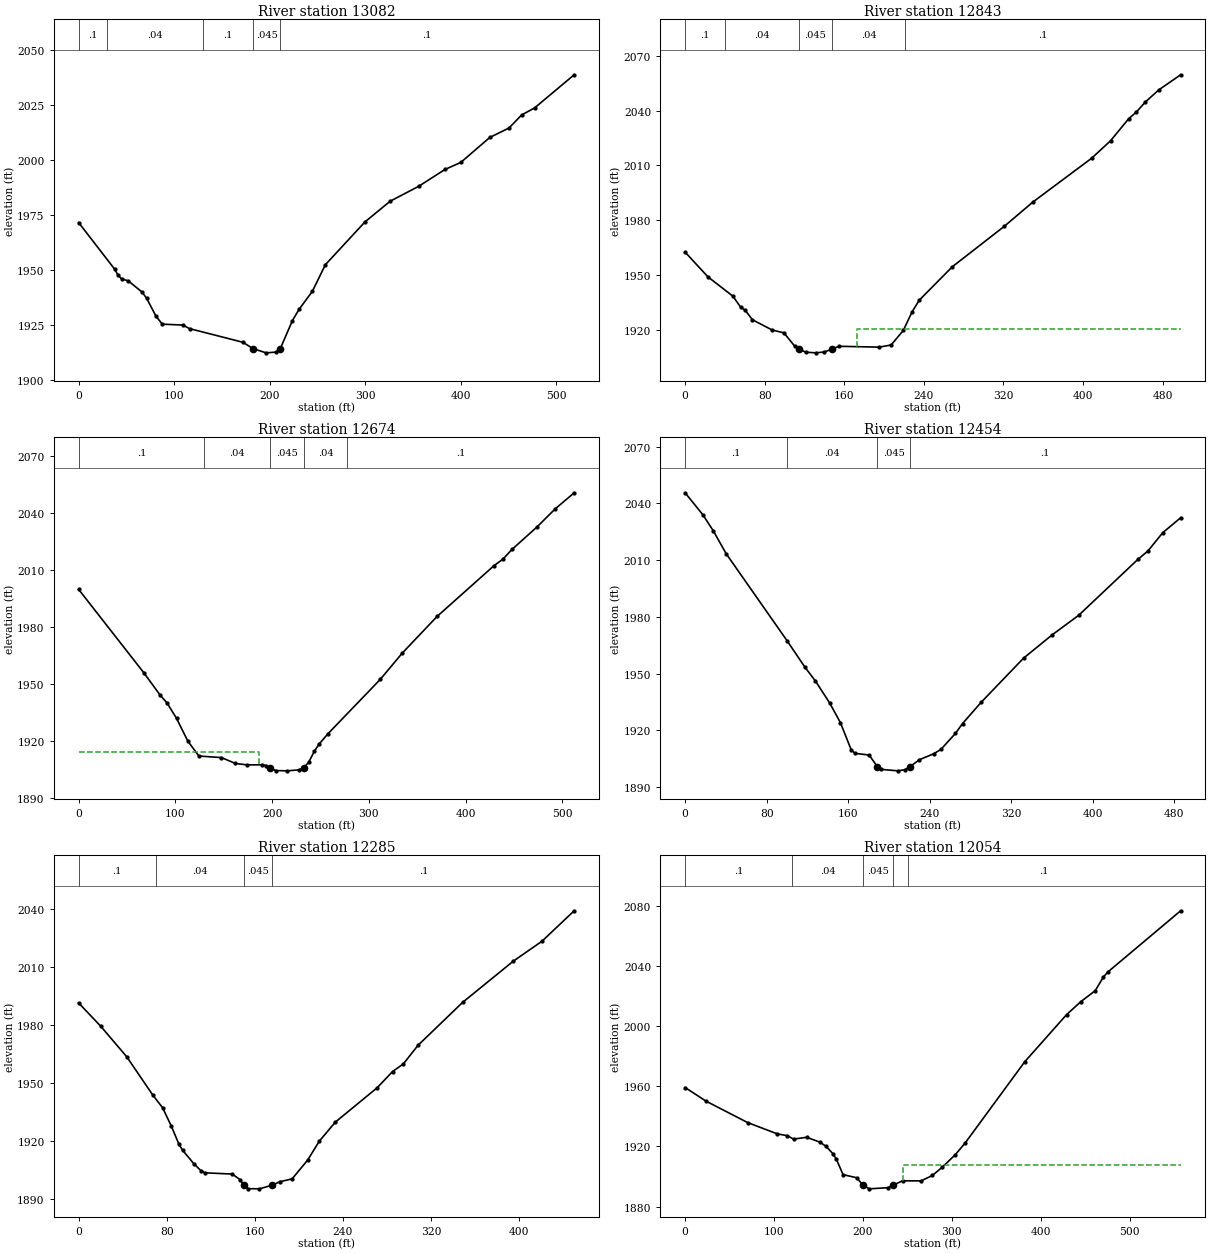
Type RM Length L Ch R = 1 ,13082   ,242.5,239,233.8
XS GIS Cut Line= 4
1964735.80337812213945.9095274621964863.14803936213892.225013409
1965030.44396688213837.2920222851965231.44877531213799.837710154
#Sta/Elev= 30
       0 1971.55    37.8 1950.27    41.3 1947.55    44.9 1945.95      52 1944.97
    66.3 1939.94    71.1 1937.13    81.1 1928.81    87.6 1925.28     109 1924.87
   116.1 1923.25     172 1917.03  182.251914.187   196.2 1912.22   206.6 1912.55
  211.151914.186   223.8 1926.94   230.7    1932   244.6  1940.2   258.3 1952.37
   299.8 1971.88   326.1 1981.28   355.9 1988.05   383.7 1995.79     400 1998.93
   430.4 2010.33   450.5 2014.62   463.8 2020.59   477.2 2023.74   518.7 2038.86
#Mann= 5 ,-1 , 0
       0      .1       0      30     .04       0     130      .1       0
  182.25    .045       0  211.15      .1       0
Bank Sta=182.25,211.15
XS Rating Curve= 0 ,0
Exp/Cntr(USF)=0,0
Exp/Cntr=0.3,0.1

Type RM Length L Ch R = 1 ,12843   ,171,168.8,161.9
XS GIS Cut Line= 4
1964858.15413108214160.6475836751964949.29295726 214116.95088619
1965109.09802235214035.7998765741965292.62415179  213918.4430319
#Sta/Elev= 30
       0 1962.68      23 1949.13    48.1 1938.58    55.7 1932.67    60.4 1930.89
    67.7 1925.72    87.4 1920.14    99.4 1918.54   110.4 1911.11  114.371909.666
   121.5 1907.98   131.4 1907.64   139.9 1908.11  147.611909.666   154.6 1911.22
   195.1 1910.76   207.1 1911.94   219.3 1919.86   228.2 1930.07   235.5 1936.49
   268.6 1954.67   320.7  1976.7   349.7 1990.08   408.6 2013.94   427.6 2023.47
   445.7 2035.44   453.7 2039.26   462.7 2044.72   476.2 2051.33   498.1 2059.56
#Mann= 5 ,-1 , 0
       0      .1       0      40     .04       0  114.37    .045       0
  147.61     .04       0  221.07      .1       0
#XS Ineff= 2 , 0
                          172.64         1920.49
Permanent Ineff=
       F       F
Bank Sta=114.37,147.61
XS Rating Curve= 0 ,0
Exp/Cntr(USF)=0,0
Exp/Cntr=0.3,0.1

Type RM Length L Ch R = 1 ,12674   ,214.2,220.4,228.9
XS GIS Cut Line= 4
1964933.06275534214319.2041716921965059.15893951214224.319914296
1965164.03101347214145.665858823 1965326.3330327213992.103179089
#Sta/Elev= 30
       0  1999.9    67.7 1955.78    84.1  1944.3    91.5 1939.99   101.2 1931.97
   112.9 1919.96   124.3 1912.11   147.7 1911.29   162.1 1908.19   174.4 1907.43
   189.9  1907.5   194.1 1907.07  197.851905.749   203.9 1904.45   215.4 1904.31
   227.4 1904.78  232.511905.749   237.8  1908.8   243.8 1914.72   248.7 1918.47
   257.8 1923.86   311.9 1952.52   334.7  1966.4   370.6 1985.65   429.3 2012.34
   438.4 2015.74   448.4 2021.11     474 2032.85   492.5 2042.22   512.3 2050.79
#Mann= 5 ,-1 , 0
       0      .1       0     130     .04       0  197.85    .045       0
  232.51     .04       0  277.81      .1       0
#XS Ineff= 2 , 0
          186.53 1914.48
Permanent Ineff=
       F       F
Bank Sta=197.85,232.51
XS Rating Curve= 0 ,0
Exp/Cntr(USF)=0,0
Exp/Cntr=0.3,0.1

Type RM Length L Ch R = 1 ,12454   ,170.3,169.4,167.5
XS GIS Cut Line= 4
1964970.51706747214466.5244660711965097.86172871214425.324722728
1965231.44877531214372.8886857461965417.47185889214278.004428349
#Sta/Elev= 30
       0 2045.55    17.5 2033.87    27.8 2025.32    40.4 2013.26     100 1967.39
   117.5 1953.42   127.8 1946.12   141.9 1934.41   152.4 1924.04   162.9 1909.77
   166.5 1907.86   180.6 1906.92   188.71900.714   192.4 1899.36   208.8 1898.58
   215.8 1899.17  220.521900.716   229.9 1904.47     244 1907.61   251.1 1909.95
   265.2 1918.34   272.2 1923.56   290.4 1934.76   332.1 1958.15   360.4 1970.56
   386.2  1980.8   444.3 2010.37   454.1 2014.78   468.7 2024.49   486.2 2032.33
#Mann= 4 ,-1 , 0
       0      .1       0     100     .04       0   188.7    .045       0
  220.52      .1       0
Bank Sta=188.7,220.52
XS Rating Curve= 0 ,0
Exp/Cntr(USF)=0,0
Exp/Cntr=0.3,0.1

Type RM Length L Ch R = 1 ,12285   ,231.2,230.6,227.4
XS GIS Cut Line= 4
1965082.88000386214595.1176043841965203.98227975214562.657200538
1965318.84217028214510.2211635561965482.39266658214397.858227166
#Sta/Elev= 30
       0 1991.42      20 1979.45    43.6 1963.71    67.3 1943.94    76.3 1937.32
    84.3 1927.73    91.1  1918.5    94.5 1915.37   104.7 1908.41   111.5 1904.62
   114.9 1903.76   139.5 1903.11   146.7 1900.22  149.841897.436   153.9 1895.58
   164.2 1895.49  176.091897.434   182.8 1899.17   193.9 1900.63     208 1910.31
   218.6  1920.1   233.3 1929.99   271.2 1947.68   285.1    1956     295 1959.99
   308.3 1969.58   348.8 1991.73   394.8 2012.98   420.8 2023.25   450.1 2038.99
#Mann= 4 ,-1 , 0
       0      .1       0      70     .04       0  149.84    .045       0
  176.09      .1       0
Bank Sta=149.84,176.09
XS Rating Curve= 0 ,0
Exp/Cntr(USF)=0,0
Exp/Cntr=0.3,0.1

Type RM Length L Ch R = 1 ,12054   ,219.7,214.2,195.5
XS GIS Cut Line= 4
1965147.80081155214849.8069268691965263.90917915214789.880027461
1965486.13809779214671.2747057161965596.00408004214535.190704976
#Sta/Elev= 30
       0  1959.2    23.4  1950.2    70.3 1935.92   103.5 1928.43   115.2 1927.14
     122 1924.92   136.8 1926.12   151.7 1922.88   158.6 1920.08   166.2 1915.25
   170.3 1911.41   177.7  1901.3   192.9 1899.24  200.271894.228   207.4 1891.85
   228.3 1892.63  233.791894.226   244.6 1897.19   265.6 1897.15   278.1 1900.73
   289.3 1906.21   304.1 1914.62   315.3 1922.51   382.2 1976.41   429.1  2007.6
   445.2 2016.28   461.4 2023.56   470.5 2032.58   475.3 2035.86   557.5  2076.7
#Mann= 5 ,-1 , 0
       0      .1       0     120     .04       0  200.27    .045       0
  233.79     .04       0  250.66      .1       0
#XS Ineff= 2 , 0
                          244.99         1907.95
Permanent Ineff=
       F       F
Bank Sta=200.27,233.79
XS Rating Curve= 0 ,0
Exp/Cntr(USF)=0,0
Exp/Cntr=0.3,0.1

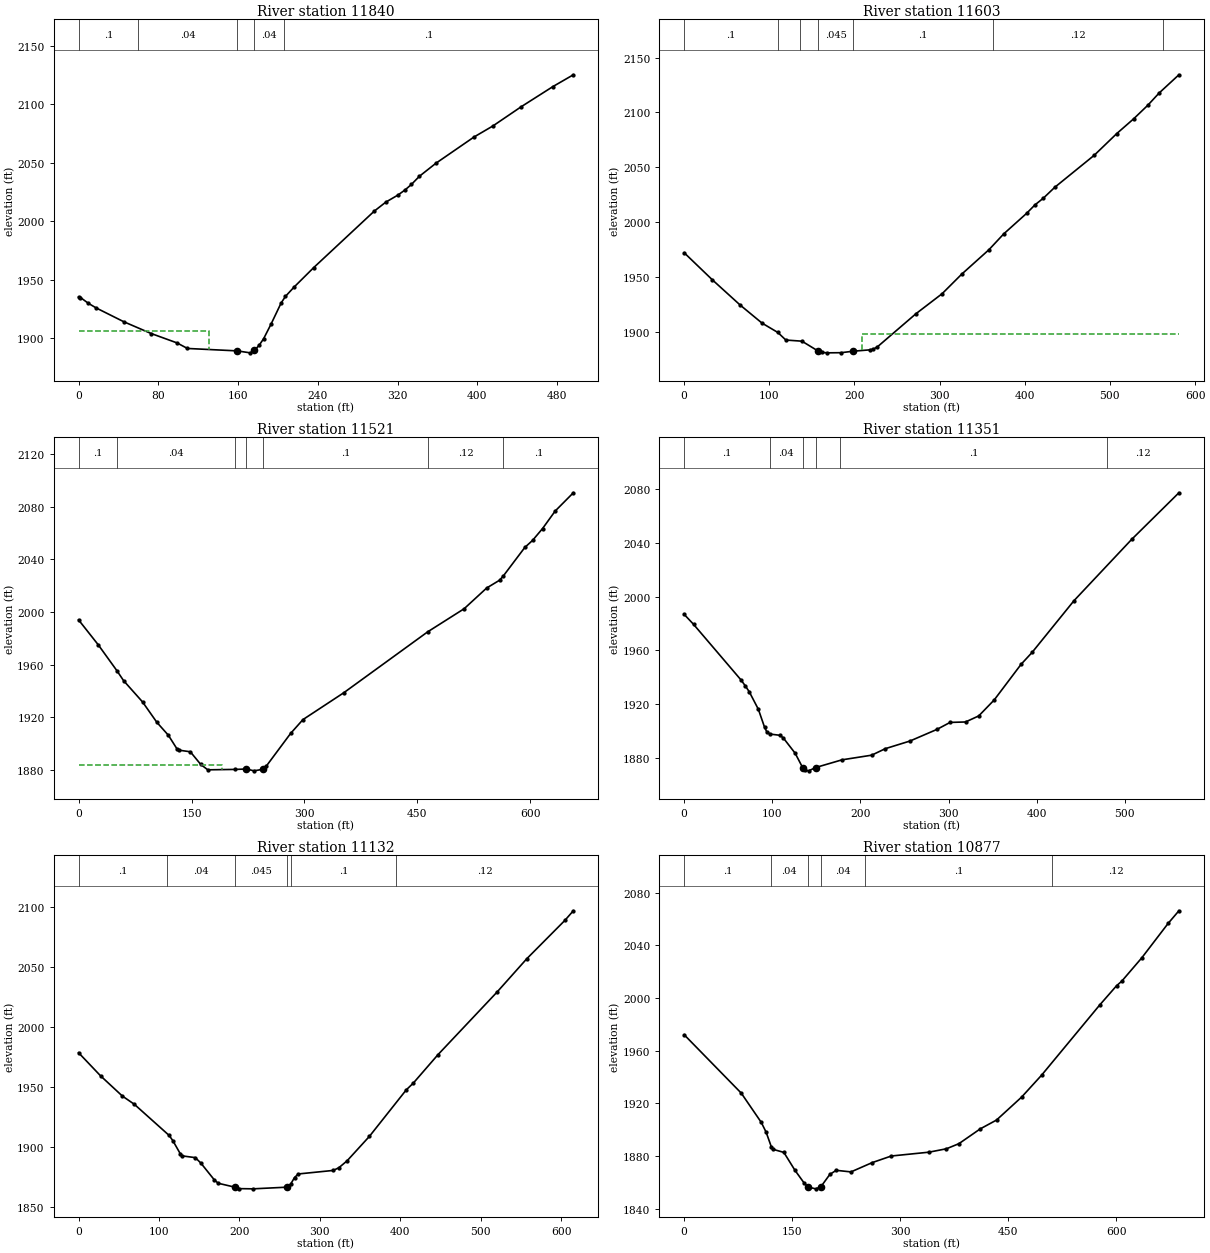
Type RM Length L Ch R = 1 ,11840   ,237.3,236.7,234.4
XS GIS Cut Line= 4
 1965421.2172901214978.4000651831965491.13200608214873.527991218
1965567.28910741 214788.631550391965703.37310815214571.396540035
#Sta/Elev= 30
       0 1935.42     1.9 1934.89     9.7 1930.01    17.6 1926.01    45.5 1914.16
    72.8 1904.17    98.8 1896.14   109.2 1891.41   159.1 1889.34   172.2 1887.67
   176.41889.725   181.2 1894.18   185.6 1899.64   193.2 1912.36   203.2  1930.2
   207.6 1935.91   216.4 1943.97     236 1960.51   296.7 2008.67   308.3 2016.36
   320.6 2022.44   327.7 2026.84   333.9 2031.38     342 2038.43   358.6 2049.56
   396.7 2071.88   415.8  2081.4   444.3 2097.87     476 2115.01   496.4 2125.04
#Mann= 5 ,-1 , 0
       0      .1       0      60     .04       0   159.1    .045       0
   176.4     .04       0  206.04      .1       0
#XS Ineff= 2 , 0
          131.09 1906.29
Permanent Ineff=
       F       F
Bank Sta=159.1,176.4
XS Rating Curve= 0 ,0
Exp/Cntr(USF)=0,0
Exp/Cntr=0.3,0.1

Type RM Length L Ch R = 1 ,11603   ,84.5,82.5,79.7
XS GIS Cut Line= 4
1965562.29519912215113.2355888511965658.42793359215032.084579236
1965750.81523685214918.4731657751965793.26345726214612.596283378
#Sta/Elev= 30
       0 1972.04    33.2 1947.27    65.8 1924.31    91.4  1907.9     110 1899.35
   119.4 1892.44   138.3 1891.41   157.61882.272   161.3 1881.18   168.3 1880.78
   184.3 1880.91  198.621882.272   218.1 1883.51     222 1884.13   226.7 1886.09
   272.2 1916.44   302.9 1934.67   325.9 1952.48   357.9 1974.79   375.3 1989.24
   402.1 2007.92     412  2015.7   421.9 2021.84   435.2 2031.69   481.6 2060.93
   508.1 2080.74     528 2094.23   544.5 2106.52   557.8 2117.68     581 2134.28
#Mann= 7 ,-1 , 0
       0      .1       0     110     .04       0  135.81      .1       0
   157.6    .045       0  198.62      .1       0  362.24     .12       0
  562.24      .1       0
#XS Ineff= 2 , 0
                          208.88         1898.34
Permanent Ineff=
       F       F
Bank Sta=157.6,198.62
XS Rating Curve= 0 ,0
Exp/Cntr(USF)=0,0
Exp/Cntr=0.3,0.1

Type RM Length L Ch R = 1 ,11521   ,164.7,169.5,176.4
XS GIS Cut Line= 4
1965609.46505938215205.0241530951965734.48402534215066.304478539
  1965852.652637 214908.746329661965910.88064854214641.582511996
#Sta/Elev= 30
       0 1993.97    26.1 1975.05    50.8 1955.44    59.8 1947.79    84.9 1931.67
     104 1916.11   119.2 1906.35   130.5 1896.13   133.9 1894.94   148.4 1893.77
   162.3 1884.11   171.6 1880.05   208.3 1880.37     223 1880.67   232.9 1879.28
   245.2 1880.48   249.3 1882.86   281.6  1907.7     298 1918.22     352 1938.53
   463.8 1984.95   512.1 2002.46     542  2018.2   559.1 2024.11   564.1 2027.35
   592.7 2049.05   602.9 2054.34   616.2 2063.36     633 2076.69   657.1 2090.56
#Mann= 7 ,-1 , 0
       0      .1       0    50.8     .04       0   208.3      .1       0
     223    .045       0   245.2      .1       0   463.8     .12       0
   564.1      .1       0
#XS Ineff= 2 , 0
       0     190 1883.72               0
Permanent Ineff=
       F       F
Bank Sta=223,245.2
XS Rating Curve= 0 ,0
Exp/Cntr(USF)=0,0
Exp/Cntr=0.3,0.1

Type RM Length L Ch R = 1 ,11351   ,201.3,219.1,225.5
XS GIS Cut Line= 4
 1965727.0941725215293.0162870761965793.26345726215221.853094029
1965891.89314587215092.0114786441966087.90404602 214863.54017465
#Sta/Elev= 30
       0 1986.87    10.6 1979.48    64.4 1938.05    69.3 1933.61    73.9 1929.11
    84.2 1916.06    91.2 1902.72    93.8 1899.24    97.1 1897.66   108.2 1896.75
   112.3  1894.9   125.9 1883.36  134.371872.682   136.9 1870.74   141.2 1870.22
  149.141872.679   179.1 1878.43   212.7 1881.89   228.2 1886.75   256.1 1892.43
   286.6 1901.06   301.7 1906.33   319.2 1906.65   334.2 1911.17   351.8 1923.12
   382.3 1949.69   394.7 1958.48   442.2 1997.03   507.6 2042.71   561.3 2077.53
#Mann= 6 ,-1 , 0
       0      .1       0   97.17     .04       0  134.37    .045       0
  149.14     .04       0  177.17      .1       0  480.23     .12       0
Bank Sta=134.37,149.14
XS Rating Curve= 0 ,0
Exp/Cntr(USF)=0,0
Exp/Cntr=0.3,0.1

Type RM Length L Ch R = 1 ,11132   ,220.9,254.6,254.4
XS GIS Cut Line= 4
1965868.17208152 215422.857902461965975.54110963215299.258672431
1966106.63120208215146.9444697681966245.21215696214938.448798911
#Sta/Elev= 30
       0 1978.62    27.3 1959.39    54.4 1942.55    69.3 1935.69   112.6 1909.73
   117.2 1905.35   126.5 1894.39   128.9  1892.7   145.1 1891.26   151.9 1886.79
   168.4    1873   173.5 1869.92  194.191866.672   199.5 1865.45   216.8 1865.27
  259.611866.673   263.8 1869.41   268.4 1874.65   273.1 1877.66   316.4 1880.59
   323.4 1882.79   333.6 1888.49   361.5 1908.96   407.4 1947.76   415.9 1953.19
   446.8 1977.05     520 2029.02   557.1 2056.88   604.4 2088.78     615 2096.85
#Mann= 6 ,-1 , 0
       0      .1       0     110     .04       0  194.19    .045       0
  259.61     .04       0  263.72      .1       0  394.68     .12       0
Bank Sta=194.19,259.61
XS Rating Curve= 0 ,0
Exp/Cntr(USF)=0,0
Exp/Cntr=0.3,0.1

Type RM Length L Ch R = 1 ,10877   ,263,248.5,228.1
XS GIS Cut Line= 4
1965950.57156821215586.4083987621966046.70430267 215496.51804965
1966157.81876199215396.6398839691966292.65428566215013.357423171
#Sta/Elev= 30
       0 1972.14    79.3 1927.76   107.1 1905.52   113.9    1898     121 1887.06
   122.9 1885.12   138.5 1882.69   153.9  1869.1   167.1 1859.08  172.111856.407
   182.6    1855  189.661856.403   202.4 1865.99   211.2 1869.08   231.7 1867.87
   261.2 1874.94   287.8 1879.96     340 1882.86   364.3 1885.45   381.7 1889.34
   411.3 1900.57   433.9 1907.28   468.7  1924.7   496.5 1941.37   577.2  1994.7
   600.8 2009.45   607.8 2012.78   635.6 2030.51   672.4 2056.81   687.3 2066.36
#Mann= 6 ,-1 , 0
       0      .1       0     120     .04       0  172.11    .045       0
  189.66     .04       0  251.61      .1       0  511.02     .12       0
Bank Sta=172.11,189.66
XS Rating Curve= 0 ,0
Exp/Cntr(USF)=0,0
Exp/Cntr=0.3,0.1