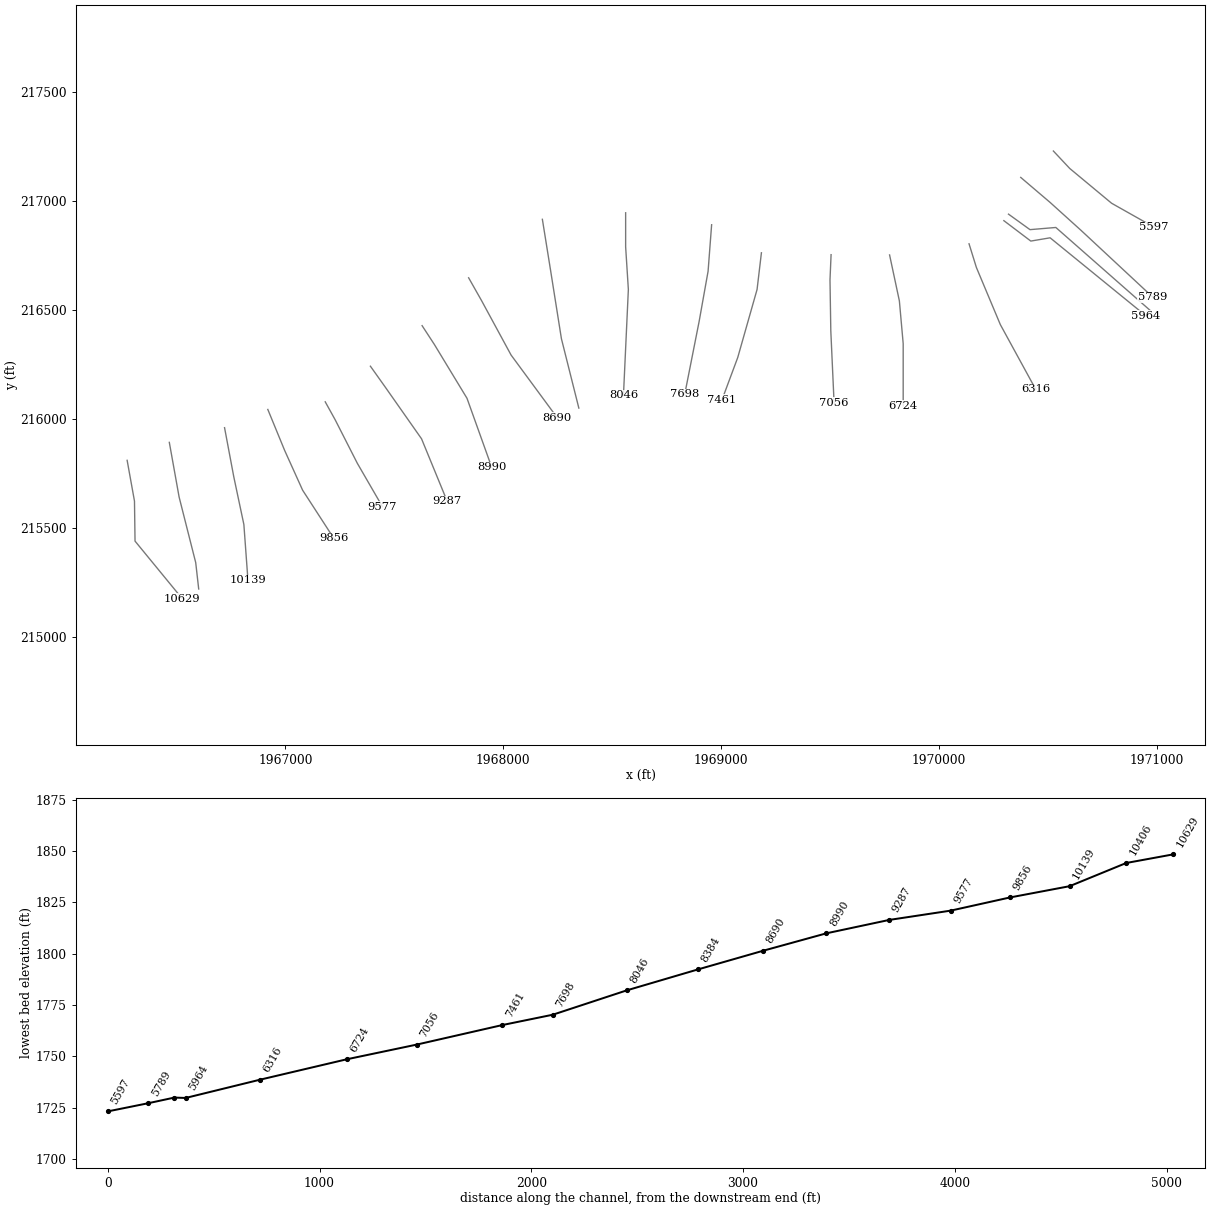
HEC-RAS study SUCKCK.prj: SUCKCK

--- SUCKCK.g01 (geometry) --- (continued)

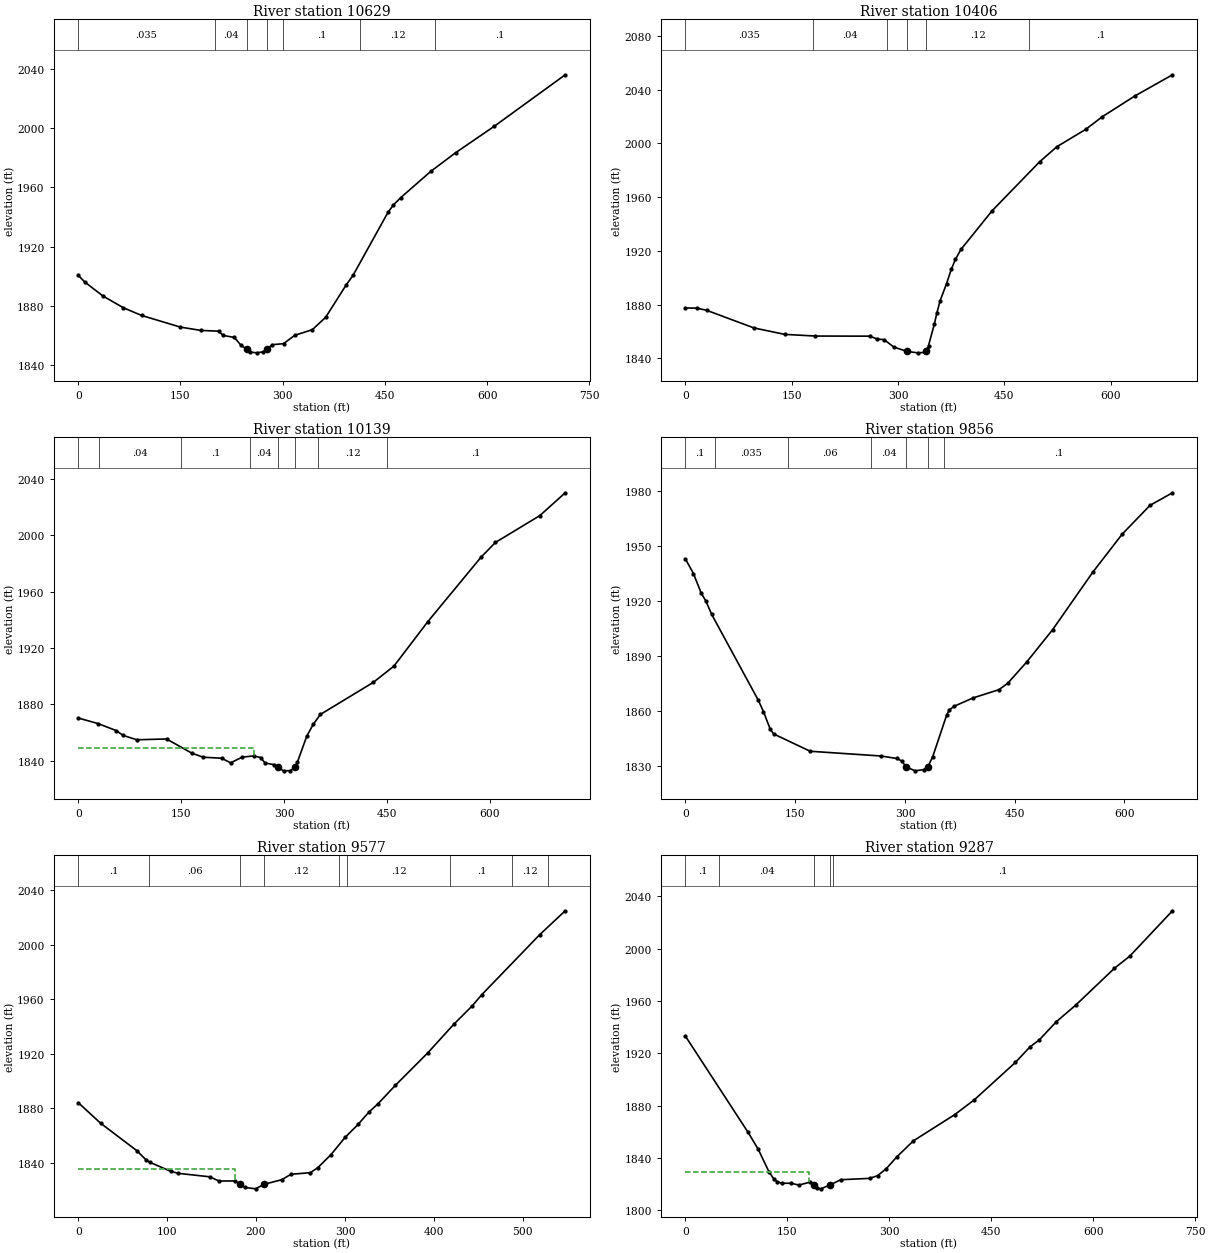
Type RM Length L Ch R = 1 ,10629   ,217.3,223,228.5
XS GIS Cut Line= 4
 1966273.9271296215809.8857944721966307.63601051215622.614233821
1966310.13296466215439.0881043831966526.11949794215175.659442402
#Sta/Elev= 30
       0 1900.69     9.7 1896.08    36.4 1886.66    66.4 1878.71      93 1873.56
   149.7 1865.72   179.7 1863.46   206.1 1862.94   212.7 1860.06   229.1 1858.72
   238.9 1853.36  247.31 1850.82   252.1 1848.87   261.9 1848.32   271.7 1849.03
   276.9 1850.82   284.9  1853.8   301.3 1854.55   317.7 1860.16   343.5 1863.96
     363 1872.29   393.3 1894.26   403.1 1900.55   454.6 1943.24   462.5 1948.18
   473.2  1953.1   517.5  1970.9   553.7 1983.39   610.6 2001.31   714.5 2036.01
#Mann= 7 ,-1 , 0
       0    .035       0  200.28     .04       0  247.31    .045       0
   276.9     .04       0  300.28      .1       0  413.82     .12       0
  523.82      .1       0
Bank Sta=247.31,276.9
XS Rating Curve= 0 ,0
Exp/Cntr(USF)=0,0
Exp/Cntr=0.3,0.1

Type RM Length L Ch R = 1 ,10406   ,266.5,267.4,264.9
XS GIS Cut Line= 4
 1966467.4410756215892.2852811581966512.38625016215641.341389886
1966588.54335149215340.4584157741966602.27659927215219.356139887
#Sta/Elev= 30
       0 1877.55    16.7 1877.32    30.1  1875.7    96.7 1862.62   140.1 1857.84
   183.4 1856.59   260.1 1856.51   270.2 1854.44   280.4 1853.89     294 1848.39
   312.61845.178   327.8  1844.1     338 1844.45  339.17 1845.18   341.4 1846.61
     343 1849.52   351.2 1865.54   354.9 1874.11   359.3 1882.76   368.4 1895.58
   375.2 1906.44   380.9 1913.62   388.7 1921.01   432.7 1949.82   499.7 1986.22
   524.1 1997.47   564.6 2010.31   588.2 2019.78   634.1 2035.22   687.2 2050.99
#Mann= 6 ,-1 , 0
       0    .035       0     180     .04       0  284.94      .1       0
   312.6    .045       0  339.17     .12       0  484.94      .1       0
Bank Sta=312.6,339.17
XS Rating Curve= 0 ,0
Exp/Cntr(USF)=0,0
Exp/Cntr=0.3,0.1

Type RM Length L Ch R = 1 ,10139   ,276.9,282.4,287.1
XS GIS Cut Line= 4
1966720.88192102215959.7030429921966763.33014143215733.728693141
1966809.52379306215515.2452057151966828.25094912215259.307406159
#Sta/Elev= 30
       0 1870.31    28.6  1866.4    55.3 1861.41    65.3    1858    85.4 1854.86
   128.8 1855.43   165.5 1845.39   182.2 1842.47   208.9 1841.78   222.2  1838.5
   239.1 1842.55   255.7 1843.38   265.8 1842.27   272.5 1838.32   285.9 1837.15
  290.57 1835.27   299.3 1832.81   309.4 1832.93  315.751835.273   319.5 1838.93
   333.2 1857.48   342.9 1866.03     353 1872.84   430.1 1895.59   460.2 1907.13
   509.5 1938.65     587 1984.36   608.2 1994.94   672.9 2013.98   709.9 2030.18
#Mann= 8 ,-1 , 0
       0      .1       0      30     .04       0     150      .1       0
  249.93     .04       0  290.57    .045       0  315.75     .04       0
  349.93     .12       0  449.93      .1       0
#XS Ineff= 2 , 0
          256.73 1849.12
Permanent Ineff=
       F       F
Bank Sta=290.57,315.75
XS Rating Curve= 0 ,0
Exp/Cntr(USF)=0,0
Exp/Cntr=0.3,0.1

Type RM Length L Ch R = 1 ,9856    ,277.6,278.9,280.2
XS GIS Cut Line= 4
1966919.38977531 216043.351006751966996.79535371215854.830969028
1967079.19484039215672.5533166611967221.52122649215452.821352165
#Sta/Elev= 30
       0 1942.87    10.9 1934.93    21.5 1924.29      28 1919.87    35.7 1912.76
    99.6 1865.78   106.6 1859.64     116  1849.9   120.8 1847.39   170.5 1837.99
   267.2 1835.41   288.8 1834.05     296 1832.62   301.21829.485     314 1827.31
   325.5 1827.98  331.211829.484   337.9    1835   357.2 1857.96   360.8  1860.6
   367.6  1862.6   393.2  1867.1   428.5  1871.6   440.4 1875.05   466.5 1886.74
   501.8 1904.31   556.6 1935.63   596.9 1956.44   634.9 1972.13   665.6 1978.99
#Mann= 7 ,-1 , 0
       0      .1       0      40    .035       0     140     .06       0
  253.79     .04       0   301.2    .045       0  331.21     .04       0
  353.79      .1       0
Bank Sta=301.2,331.21
XS Rating Curve= 0 ,0
Exp/Cntr(USF)=0,0
Exp/Cntr=0.3,0.1

Type RM Length L Ch R = 1 ,9577    ,286.7,290.6,293.6
XS GIS Cut Line= 4
1967182.81843729216078.3083647381967227.76361184215997.157355123
1967330.13873167215796.152546691 1967444.9986222215597.644692401
#Sta/Elev= 30
       0 1884.22    25.2 1869.09    66.1 1848.85      76 1842.36    80.8 1840.34
   103.8 1833.86   112.4 1832.31     148 1829.76   158.3 1826.66   175.8 1826.69
  182.281824.322   187.2    1822   199.5 1820.92  209.31 1824.32     229 1827.63
   239.3 1831.61   261.2 1832.79   269.5  1836.5   284.2 1845.97   300.2 1858.73
   314.9 1868.31   326.9 1877.27   337.1 1883.35   356.7 1896.92   393.1 1920.73
   422.2 1941.62   443.1 1955.27   453.7 1963.35     519 2007.53   547.7 2025.08
#Mann= 9 ,-1 , 0
       0      .1       0      80     .06       0  182.28    .045       0
  209.31     .12       0  292.77      .1       0  302.77     .12       0
  418.34      .1       0  488.34     .12       0  528.34      .1       0
#XS Ineff= 2 , 0
          176.22 1835.32
Permanent Ineff=
       F       F
Bank Sta=182.28,209.31
XS Rating Curve= 0 ,0
Exp/Cntr(USF)=0,0
Exp/Cntr=0.3,0.1

Type RM Length L Ch R = 1 ,9287    ,297.8,296.3,292
XS GIS Cut Line= 4
1967390.06563108 216241.858861041967457.48339291216146.974603643
1967624.77932042215908.515483081 1967742.1361651215622.614233821
#Sta/Elev= 30
       0 1933.11    92.2 1859.56     107 1846.73     123 1829.33   129.8 1824.13
   134.5    1822   141.6 1820.66   155.1 1820.68   167.1 1819.28   183.1 1821.52
   188.7 1819.17   193.4 1817.02   199.2 1816.39  212.531819.346   228.7 1823.38
   271.3  1824.4   282.9  1826.5   295.4 1831.74   311.4 1841.05   335.4 1853.07
     396 1873.06   425.3 1884.56   485.6 1913.08   506.9 1924.93   520.5 1930.18
     546  1944.3   574.3 1956.88     631 1984.93   653.9 1994.37   716.7 2029.04
#Mann= 5 ,-1 , 0
       0      .1       0      50     .04       0   188.7    .045       0
  212.53     .04       0   216.4      .1       0
#XS Ineff= 2 , 0
          182.23 1829.25
Permanent Ineff=
       F       F
Bank Sta=188.7,212.53
XS Rating Curve= 0 ,0
Exp/Cntr(USF)=0,0
Exp/Cntr=0.3,0.1

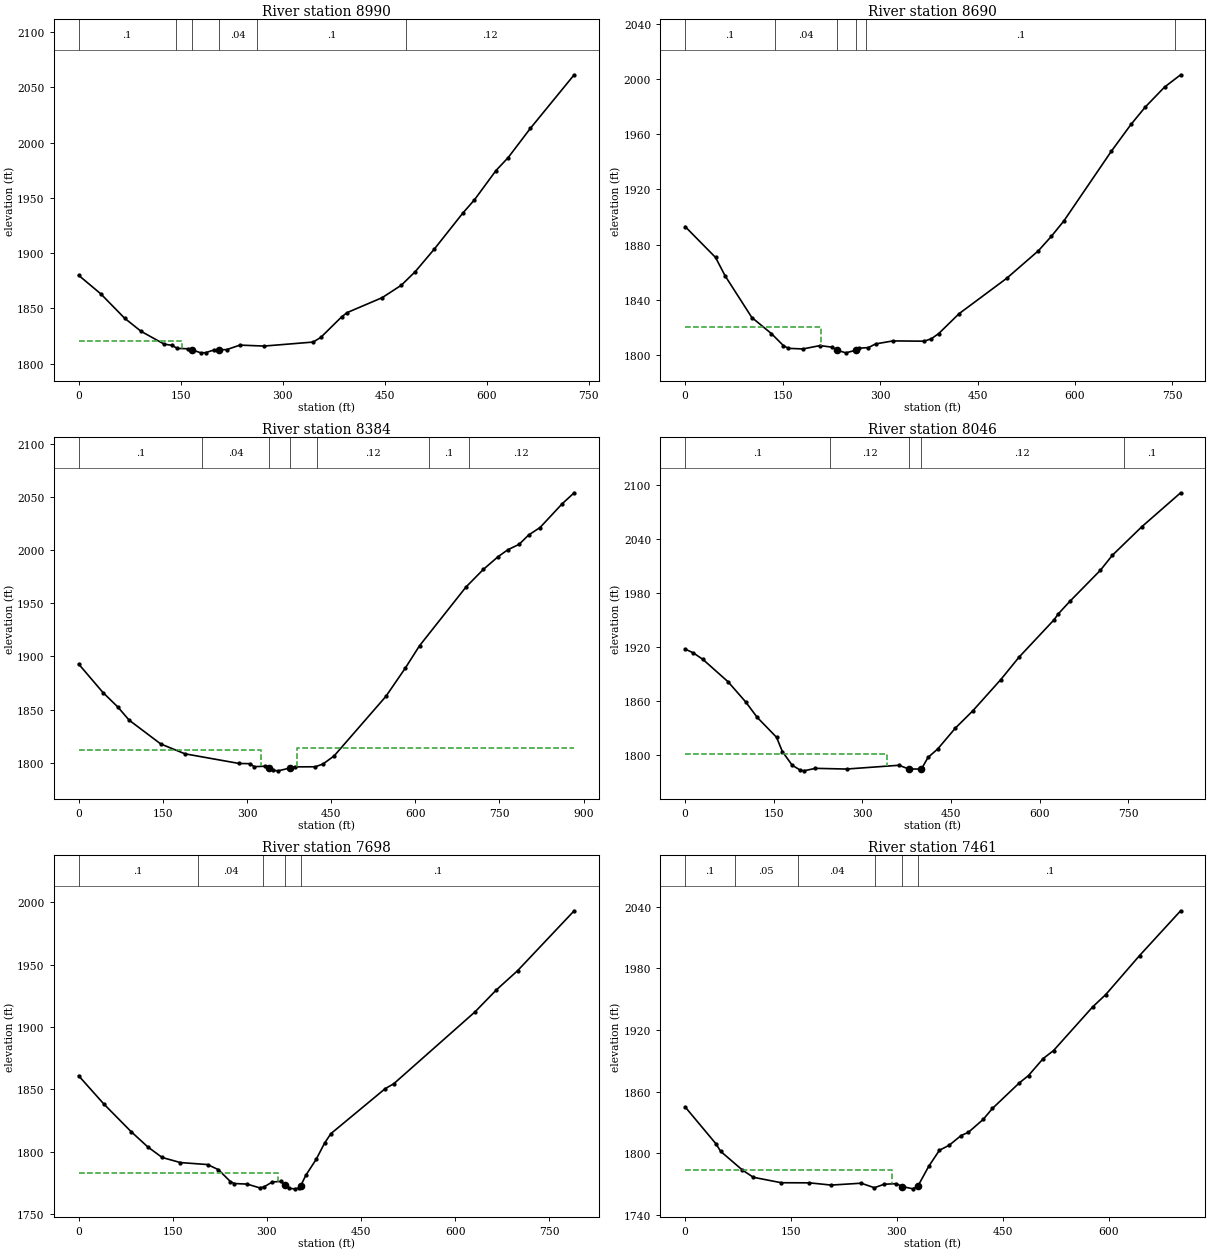
Type RM Length L Ch R = 1 ,8990    ,300.3,300.1,297.8
XS GIS Cut Line= 4
1967627.27627457216427.8819446191967683.45774276 216341.73702672
1967833.27499128216094.5385666611967946.88640474215777.425390626
#Sta/Elev= 30
       0    1880    32.4 1863.33    67.7 1841.17    91.8 1829.35   125.9 1817.71
   137.4 1816.66   145.1 1813.89   160.5 1813.57  167.431812.519   179.6 1809.88
   186.9 1810.05   198.8 1812.43  205.73 1812.52   217.9 1812.81   237.2 1816.87
   272.9 1816.01   344.9 1819.63   356.1  1823.8   386.8 1842.41   394.9 1846.27
   446.5  1859.8   474.5 1870.99     495 1883.26   523.2 1903.79     565 1936.22
   582.2  1948.3   613.8 1974.74   631.8 1986.51   664.3 2012.82   728.8 2061.34
#Mann= 6 ,-1 , 0
       0      .1       0  142.85     .04       0  167.43    .045       0
  205.73     .04       0  262.85      .1       0   481.9     .12       0
#XS Ineff= 2 , 0
          152.71 1820.22
Permanent Ineff=
       F       F
Bank Sta=167.43,205.73
XS Rating Curve= 0 ,0
Exp/Cntr(USF)=0,0
Exp/Cntr=0.3,0.1

Type RM Length L Ch R = 1 ,8690    ,316.4,306.4,297.8
XS GIS Cut Line= 4
1967840.76585371216647.6139091161967899.44427605216543.990312223
1968035.52827678216293.0464209511968247.76937886216004.648217549
#Sta/Elev= 30
       0 1893.08    46.9 1870.61    61.4 1857.42   102.7 1827.02   132.8 1815.35
   151.4 1806.57   158.9 1804.63   181.3 1804.18   207.4 1806.61   226.1 1805.49
  233.961803.296   247.3 1801.36  263.031803.296   267.1 1804.73   282.1 1805.17
   293.2 1807.84   319.9 1810.02   367.9 1809.82   379.1 1811.62   390.3 1815.36
   421.6 1829.78   494.9 1855.48   543.8 1875.54   563.8 1886.05     583 1897.21
   655.7 1947.58   686.3 1967.29   708.2 1979.87   737.8 1994.34   762.6 2003.28
#Mann= 6 ,-1 , 0
       0      .1       0  139.08     .04       0  233.96    .045       0
  263.03     .04       0  279.08      .1       0  754.55     .12       0
#XS Ineff= 2 , 0
          209.74 1820.42
Permanent Ineff=
       F       F
Bank Sta=233.96,263.03
XS Rating Curve= 0 ,0
Exp/Cntr(USF)=0,0
Exp/Cntr=0.3,0.1

Type RM Length L Ch R = 1 ,8384    ,343.4,337.6,331.8
XS GIS Cut Line= 4
1968179.10313995216916.0364793821968217.80592915216675.080404678
1968266.49653492216367.9550452111968346.39906746216049.593392105
#Sta/Elev= 30
       0 1892.81    43.4 1865.97      70  1852.3    89.9 1840.04   146.4 1817.57
   189.6 1808.31     286 1799.24   305.9 1799.03   312.6 1796.22   332.5 1796.66
  340.041794.973   345.8 1792.77   355.7 1792.31  376.651794.974   385.6 1796.05
   421.6 1796.13   435.5 1798.71   455.4 1806.38   547.7  1862.4   582.1 1888.87
   607.6    1910   690.3 1965.18   721.2 1981.73   747.8 1993.86   765.2 2000.35
   785.1 2005.38     802 2014.15   822.3 2021.15   861.8 2043.53   883.2 2053.88
#Mann= 7 ,-1 , 0
       0      .1       0     220     .04       0  340.04    .045       0
  376.65     .04       0  424.04     .12       0  625.01      .1       0
  695.01     .12       0
#XS Ineff= 2 , 0
          325.21 1811.81  389.68         1814.13
Permanent Ineff=
       F       F
Bank Sta=340.04,376.65
XS Rating Curve= 0 ,0
Exp/Cntr(USF)=0,0
Exp/Cntr=0.3,0.1

Type RM Length L Ch R = 1 ,8046    ,349.3,348.3,343.3
XS GIS Cut Line= 4
1968561.13712368216945.9999290861968561.13712368216789.940295211
1968573.62189439216593.9293950631968551.14930711216108.271814442
#Sta/Elev= 30
       0 1917.25    13.8 1913.09    30.2 1905.78    72.8 1880.92   102.4 1858.69
     122 1841.48   154.8 1819.31   164.7 1803.34   181.1 1788.45   194.3 1783.01
   200.9 1782.07   220.6 1784.84   273.2 1784.07   361.9 1788.26   378.4 1784.15
  398.751784.031   401.4 1785.77   411.2 1797.08   427.3 1806.21   457.2 1829.39
   486.8 1848.65   534.1 1883.29     565 1908.21   624.7 1950.02   631.3 1956.19
   651.1 1970.25   702.8  2004.8   723.2 2021.53   773.2  2053.3   838.6 2090.82
#Mann= 5 ,-1 , 0
       0      .1       0  246.06     .12       0   378.4    .045       0
  398.75     .12       0  742.47      .1       0
#XS Ineff= 2 , 0
          340.97 1800.22
Permanent Ineff=
       F       F
Bank Sta=378.4,398.75
XS Rating Curve= 0 ,0
Exp/Cntr(USF)=0,0
Exp/Cntr=0.3,0.1

Type RM Length L Ch R = 1 ,7698    ,235.6,237.4,230.3
XS GIS Cut Line= 4
1968955.65587812216891.0669379621968939.42567619 216677.57735882
1968898.22593285216446.6091006841968832.05664809216112.017245655
#Sta/Elev= 30
       0 1860.93    39.9 1838.43    83.8 1816.04   110.2 1803.89   133.1  1795.4
   162.2 1791.31   205.5 1789.72   222.7 1785.63     242 1776.05   248.1  1774.5
   268.7 1774.04   288.7 1771.02   295.4 1771.78   308.7 1775.76     322 1776.19
   328.7 1773.55   335.4 1770.56   344.3 1770.25     352 1771.02  353.971772.695
     362 1781.05   378.7 1793.99     392 1806.91     402 1814.48   488.8 1850.66
   502.2 1854.49   631.7 1912.12     666 1929.86   699.5 1945.11   789.8  1993.2
#Mann= 5 ,-1 , 0
       0      .1       0     190     .04       0  294.11      .1       0
   328.7    .045       0  353.97      .1       0
#XS Ineff= 2 , 0
          317.48 1783.11
Permanent Ineff=
       F       F
Bank Sta=328.7,353.97
XS Rating Curve= 0 ,0
Exp/Cntr(USF)=0,0
Exp/Cntr=0.3,0.1

Type RM Length L Ch R = 1 ,7461    ,395.7,404.7,407.6
XS GIS Cut Line= 4
1969184.12718211216762.4737996481969164.15154897216593.929395063
1969075.50967693216281.8101273121969003.09800681216087.047704235
#Sta/Elev= 30
       0 1845.09    43.8 1809.03    50.4 1801.74    81.2 1783.53    96.7 1776.49
   136.3 1771.18   176.2 1771.08   206.9  1768.9   249.5 1770.73   268.1 1766.32
   281.9  1769.7   298.9 1770.29   307.9 1767.46   322.8 1765.24  329.931768.085
   345.1 1787.12   360.3 1802.82     374 1807.65     391 1817.16   401.3 1820.28
   422.2 1832.81   435.4 1843.56   473.3 1868.32   486.5 1875.63   507.3 1892.16
     522 1899.96   577.3 1942.41     596 1954.54   643.8 1992.46     702 2036.09
#Mann= 6 ,-1 , 0
       0      .1       0      70     .05       0     160     .04       0
  269.72      .1       0   307.9    .045       0  329.93      .1       0
#XS Ineff= 2 , 0
          293.41 1783.77
Permanent Ineff=
       F       F
Bank Sta=307.9,329.93
XS Rating Curve= 0 ,0
Exp/Cntr(USF)=0,0
Exp/Cntr=0.3,0.1

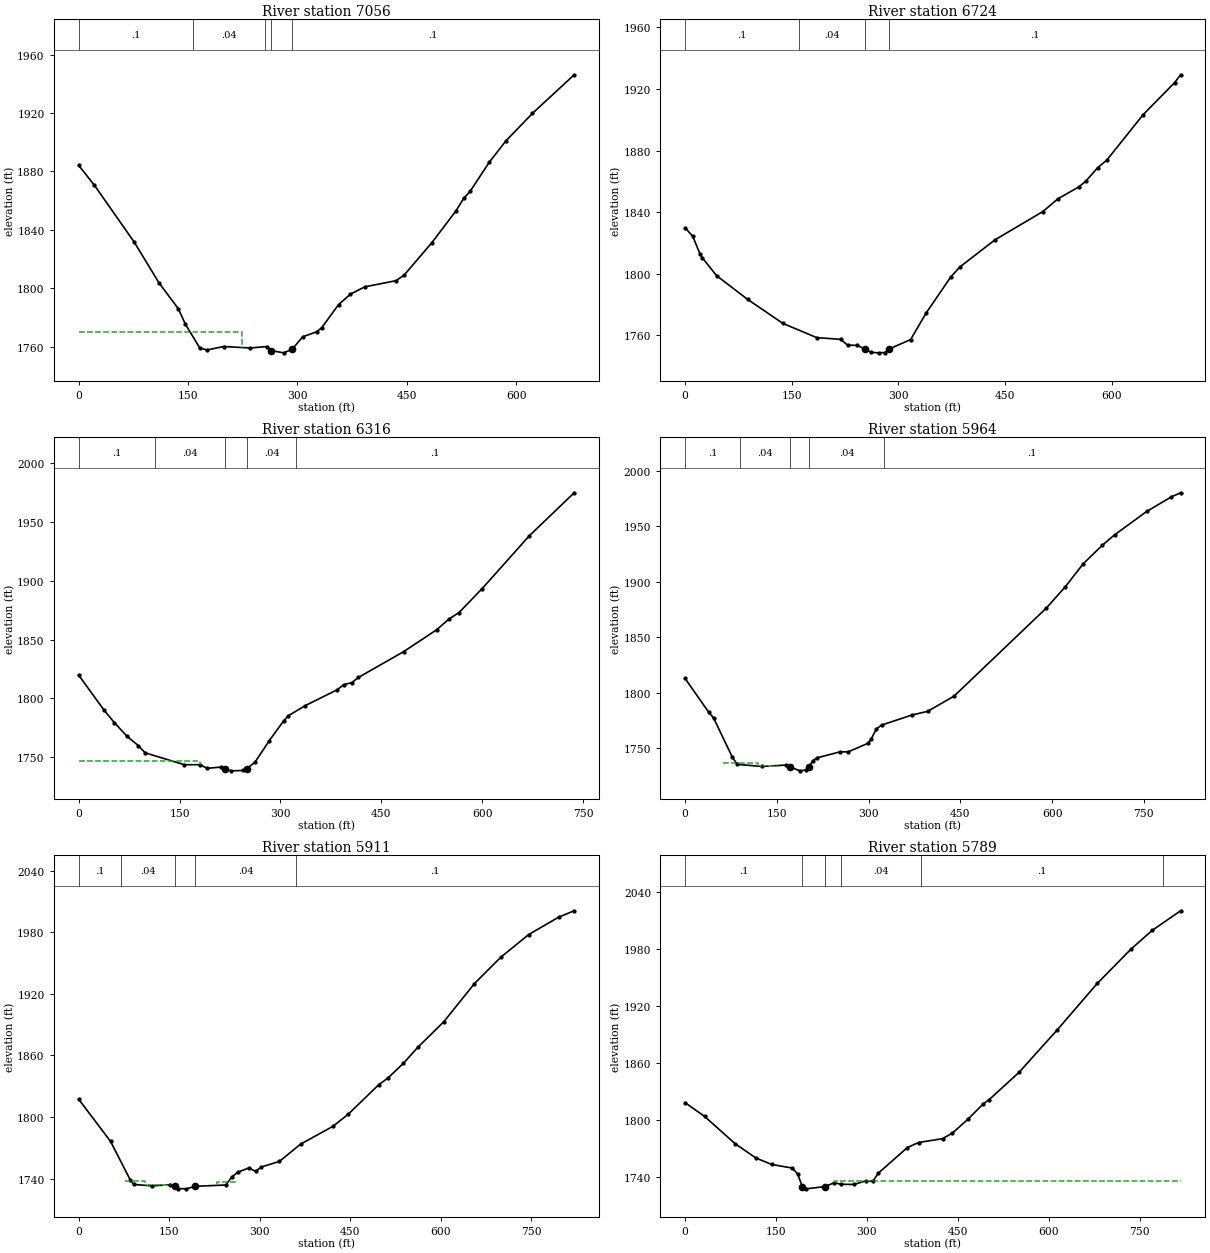
Type RM Length L Ch R = 1 ,7056    ,329.9,331.7,331.8
XS GIS Cut Line= 4
1969503.73731229216753.734460151  1969498.743404216637.626092548
1969502.48883522 216404.160880271969517.47056007216074.562933525
#Sta/Elev= 30
       0 1884.25    21.7 1870.52    76.4  1831.5   110.3 1803.63   136.6 1786.04
   146.4 1775.39   166.1 1759.07     176 1757.67   198.9 1760.06     235 1759.04
     258 1760.03   264.5 1757.25     281 1755.72  292.861758.124   307.2 1766.71
   326.4 1770.12   333.5    1773   356.4 1788.73   372.8 1795.95   392.6 1800.97
   435.2 1805.15   446.4 1808.99   484.1 1831.01   517.4 1852.95     528 1861.49
   537.1  1866.5   563.3 1886.47   586.3 1901.14   622.4 1919.83   679.6 1946.27
#Mann= 5 ,-1 , 0
       0      .1       0  156.22     .04       0  256.22      .1       0
   264.5    .045       0  292.86      .1       0
#XS Ineff= 2 , 0
          224.64 1769.87
Permanent Ineff=
       F       F
Bank Sta=264.5,292.86
XS Rating Curve= 0 ,0
Exp/Cntr(USF)=0,0
Exp/Cntr=0.3,0.1

Type RM Length L Ch R = 1 ,6724    ,399.3,408.2,416.7
XS GIS Cut Line= 4
1969772.15988255 216752.485983081969817.10505711216541.493358081
 1969834.5837361216345.482457933 1969834.5837361216060.829685744
#Sta/Elev= 30
       0 1829.81    10.8 1824.24    20.8 1812.97    24.2 1810.34    44.3 1798.69
    87.9  1783.3   137.6 1767.66   185.2 1758.43   218.7 1757.32   228.6 1753.56
   241.8 1753.39  252.781751.134   261.5 1748.84   272.4 1748.54   281.3 1748.76
  287.511751.135   317.3 1757.16   338.9 1774.24   373.5 1797.66   386.7 1804.39
     436 1821.98   503.3 1840.33   524.6 1848.66   554.1 1856.39     564 1860.19
   580.4 1868.81   593.5 1873.88   644.3 1903.23   688.6 1924.08   697.2 1929.23
#Mann= 4 ,-1 , 0
       0      .1       0     160     .04       0  252.78    .045       0
  287.51      .1       0
Bank Sta=252.78,287.51
XS Rating Curve= 0 ,0
Exp/Cntr(USF)=0,0
Exp/Cntr=0.3,0.1

Type RM Length L Ch R = 1 ,6316    ,314.7,351.7,383.5
XS GIS Cut Line= 4
1970136.71518729216803.673542992 1970170.4240682216695.056037814
1970280.29005045216432.8758529031970442.59206968216135.738310004
#Sta/Elev= 30
       0 1819.85    37.2 1790.55      53 1779.59    71.4 1768.27    88.7 1760.03
      99 1753.88   157.3 1743.81   180.3 1743.86     191 1740.76   211.1 1741.81
  217.281740.621   226.5 1738.64   244.3 1738.95  250.061740.618   262.1 1745.89
   283.4 1764.25   304.8 1781.06   311.9  1785.4   336.8 1793.94   384.1 1807.31
   394.1 1811.66   406.3 1813.52   415.9 1817.85   483.2 1839.74   532.1 1858.24
   550.5 1867.38   565.5 1872.92   599.8 1893.18   670.1 1938.09   736.6 1974.45
#Mann= 5 ,-1 , 0
       0      .1       0  113.73     .04       0  217.28    .045       0
  250.06     .04       0  323.73      .1       0
#XS Ineff= 2 , 0
          180.27 1747.08
Permanent Ineff=
       F       F
Bank Sta=217.28,250.06
XS Rating Curve= 0 ,0
Exp/Cntr(USF)=0,0
Exp/Cntr=0.5,0.3

Type RM Length L Ch R = 1 ,5964    ,57.2,52.9,53.5
XS GIS Cut Line= 4
1970296.52025237216909.794094027 1970420.1194824216816.158313702
1970508.76135444216831.1400385541970946.97680637216474.075596246
#Sta/Elev= 30
       0 1812.96    38.9 1782.33    46.5 1777.47    76.9 1742.46    85.2 1735.56
   126.1  1733.7   165.1 1734.97  171.011733.207   188.4 1729.74   198.4 1730.63
  202.541733.211   208.4 1738.57   215.1 1741.37   253.5 1746.89   266.4 1746.78
   299.1 1754.58   304.3 1758.49   312.7 1767.44   321.2 1770.93   370.6 1780.01
   396.6 1783.34   439.7 1797.04   590.6  1876.4   621.7 1895.65   651.2  1916.5
   682.2 1933.04   702.1 1942.36   754.9 1963.54   795.2 1976.65   810.2  1980.3
#Mann= 5 ,-1 , 0
       0      .1       0      90     .04       0  171.01    .045       0
  202.54     .04       0  324.96      .1       0
#XS Ineff= 3 ,-1
   61.93  118.83  1736.4  122.94  152.86 1734.36     222   810.2 1734.15
Permanent Ineff=
       F       F       F
Bank Sta=171.01,202.54
XS Rating Curve= 0 ,0
Exp/Cntr(USF)=0,0
Exp/Cntr=0.5,0.3

Type RM Length L Ch R = 1 ,5911    ,140.5,122.3,96.2
XS GIS Cut Line= 4
1970317.74436258216939.7575437311970416.37405119216868.594350684
1970534.97937294216878.5821672521970970.69787072216495.299706453
#Sta/Elev= 30
       0  1817.3    52.9 1776.15    85.8 1738.34    91.4  1734.2   122.2 1732.76
   151.8 1734.11  159.551732.408     165 1730.22   178.2 1729.93  193.271732.405
   243.9 1733.69   253.8 1741.45   263.7 1746.16   281.7 1750.22   293.3 1747.03
   302.6 1751.22   332.5 1756.61   367.7 1773.46   421.2  1790.8   446.8 1802.69
   497.2  1831.4   511.9 1837.62   537.9 1852.16   561.8 1867.78   604.9 1892.68
   655.8 1929.95   699.5 1955.67   745.6  1977.7   795.2 1994.68     821  2000.9
#Mann= 5 ,-1 , 0
       0      .1       0      70     .04       0  159.55    .045       0
  193.27     .04       0  360.65      .1       0
#XS Ineff= 4 ,-1
   76.29  110.09 1737.28  113.79  152.88 1733.32  198.27  225.31 1732.44
  228.69  260.39 1736.52
Permanent Ineff=
       F       F       F       F
Bank Sta=159.55,193.27
XS Rating Curve= 0 ,0
Exp/Cntr(USF)=0,0
Exp/Cntr=0.5,0.3

Type RM Length L Ch R = 1 ,5789    ,193.1,192.3,191.6
XS GIS Cut Line= 4
1970373.92583078217108.3019483171970508.76135445216993.442057784
1970651.08774054216864.8489194711970979.43721021216558.972037075
#Sta/Elev= 30
       0  1817.9    32.1 1803.49    82.4  1774.8   116.8 1759.69   142.7 1752.89
   177.2 1749.03   185.7 1742.76  193.491729.588     195 1727.88   199.6 1727.21
  230.841729.591     246 1733.63   256.8 1732.07   278.9  1731.8   297.8  1735.6
   309.8 1735.12   318.7 1743.65   366.8 1770.67   385.2 1775.96   424.9 1780.02
   441.1 1785.91   466.7 1800.44   491.5 1816.36   501.8 1821.12   551.1 1849.87
   613.9 1894.39   680.2 1943.46   735.9  1979.6   770.8 1999.26   817.7 2019.87
#Mann= 6 ,-1 , 0
       0      .1       0  193.49    .045       0  230.84      .1       0
  257.13     .04       0  388.94      .1       0  788.94     .04       0
#XS Ineff= 2 , 0
                          245.69         1735.27
Permanent Ineff=
       F       F
Bank Sta=193.49,230.84
XS Rating Curve= 0 ,0
Exp/Cntr(USF)=0,0
Exp/Cntr=0.3,0.1

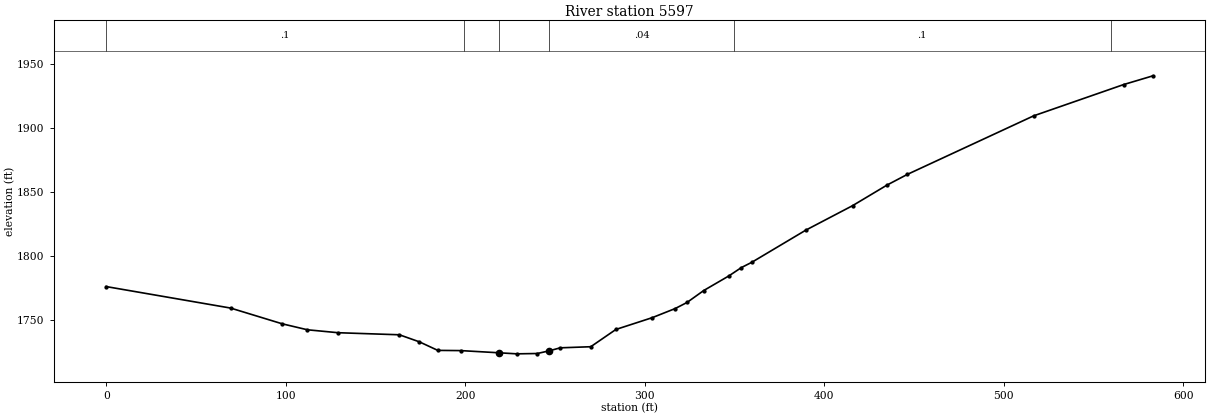
Type RM Length L Ch R = 1 ,5597    ,214.5,218.2,226.6
XS GIS Cut Line= 4
 1970523.7430793217229.4042242041970598.65170356 217149.50169166
1970790.91717249216989.6966265711970985.67959557216879.830644323
#Sta/Elev= 30
       0 1775.78    69.3 1758.98    98.1 1746.65   112.1    1742   129.2 1739.71
   163.3  1738.1   174.4  1732.6   184.7  1725.9   197.5 1725.73   218.8 1724.02
   228.7  1723.2   240.1 1723.46  246.791725.566   252.9  1727.9   269.9 1728.76
   283.9 1742.26   304.1 1751.46   316.9 1758.59   323.5 1763.35   332.8 1772.68
   346.8  1784.1   353.8 1790.65   359.6 1794.77   389.7 1819.92   415.7 1839.02
   434.9 1855.13   446.2 1863.46   516.6 1909.27   566.7 1933.71   583.1 1940.58
#Mann= 6 ,-1 , 0
       0      .1       0  199.52     .04       0   218.8    .045       0
  246.79     .04       0  349.52      .1       0  559.53     .04       0
Bank Sta=218.8,246.79
XS Rating Curve= 0 ,0
Exp/Cntr(USF)=0,0
Exp/Cntr=0.3,0.1