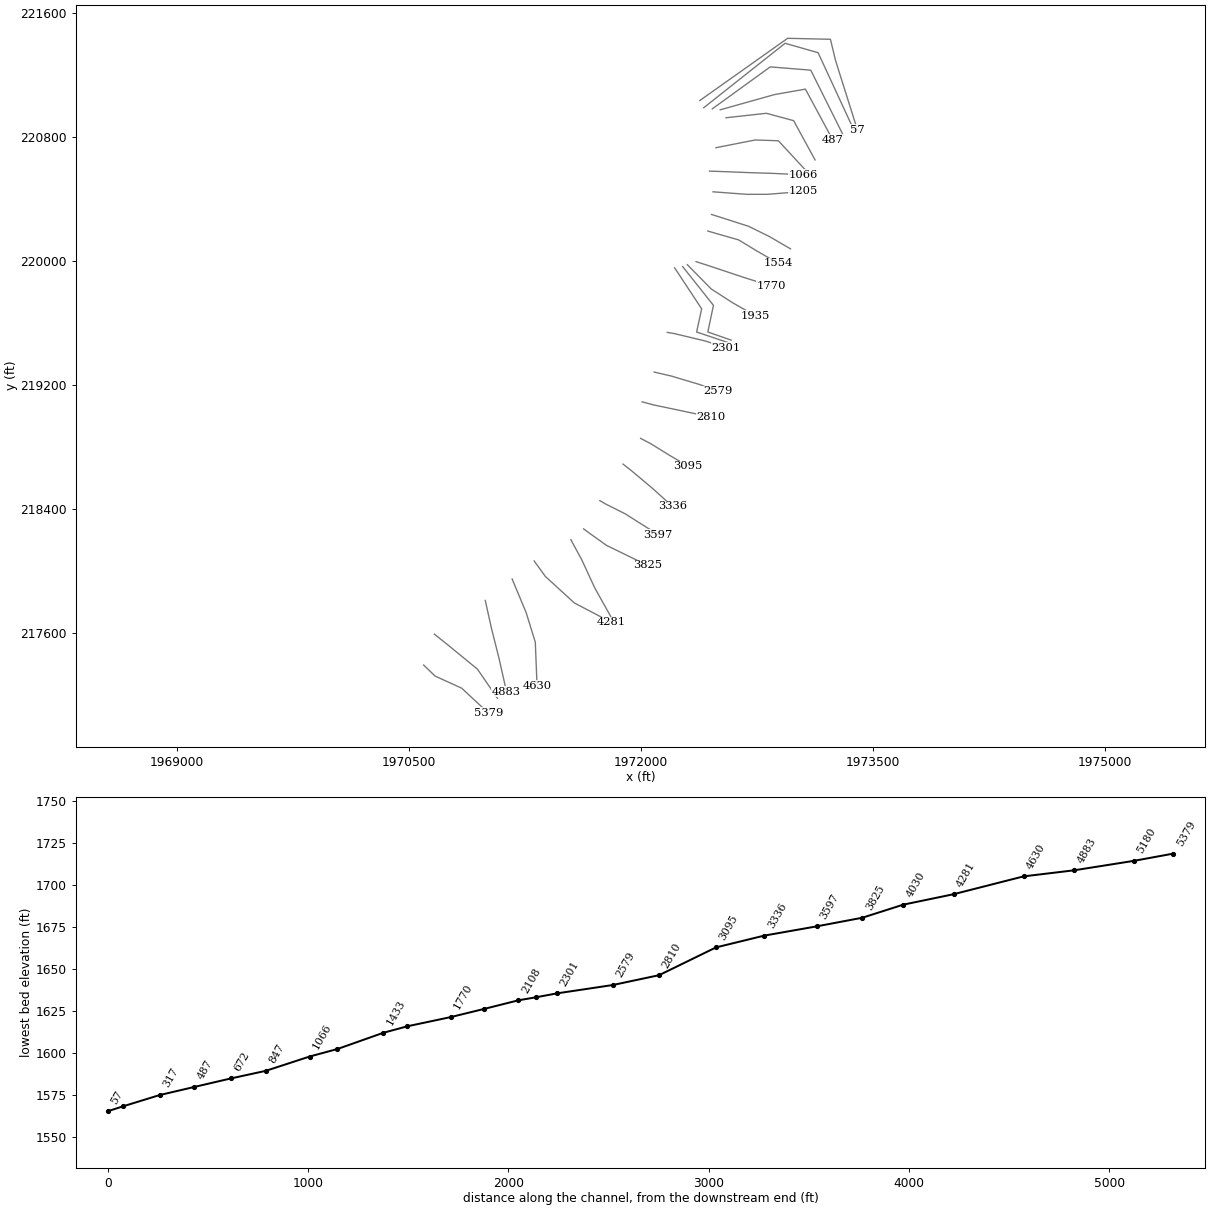
HEC-RAS study SUCKCK.prj: SUCKCK

--- SUCKCK.g01 (geometry) --- (continued)

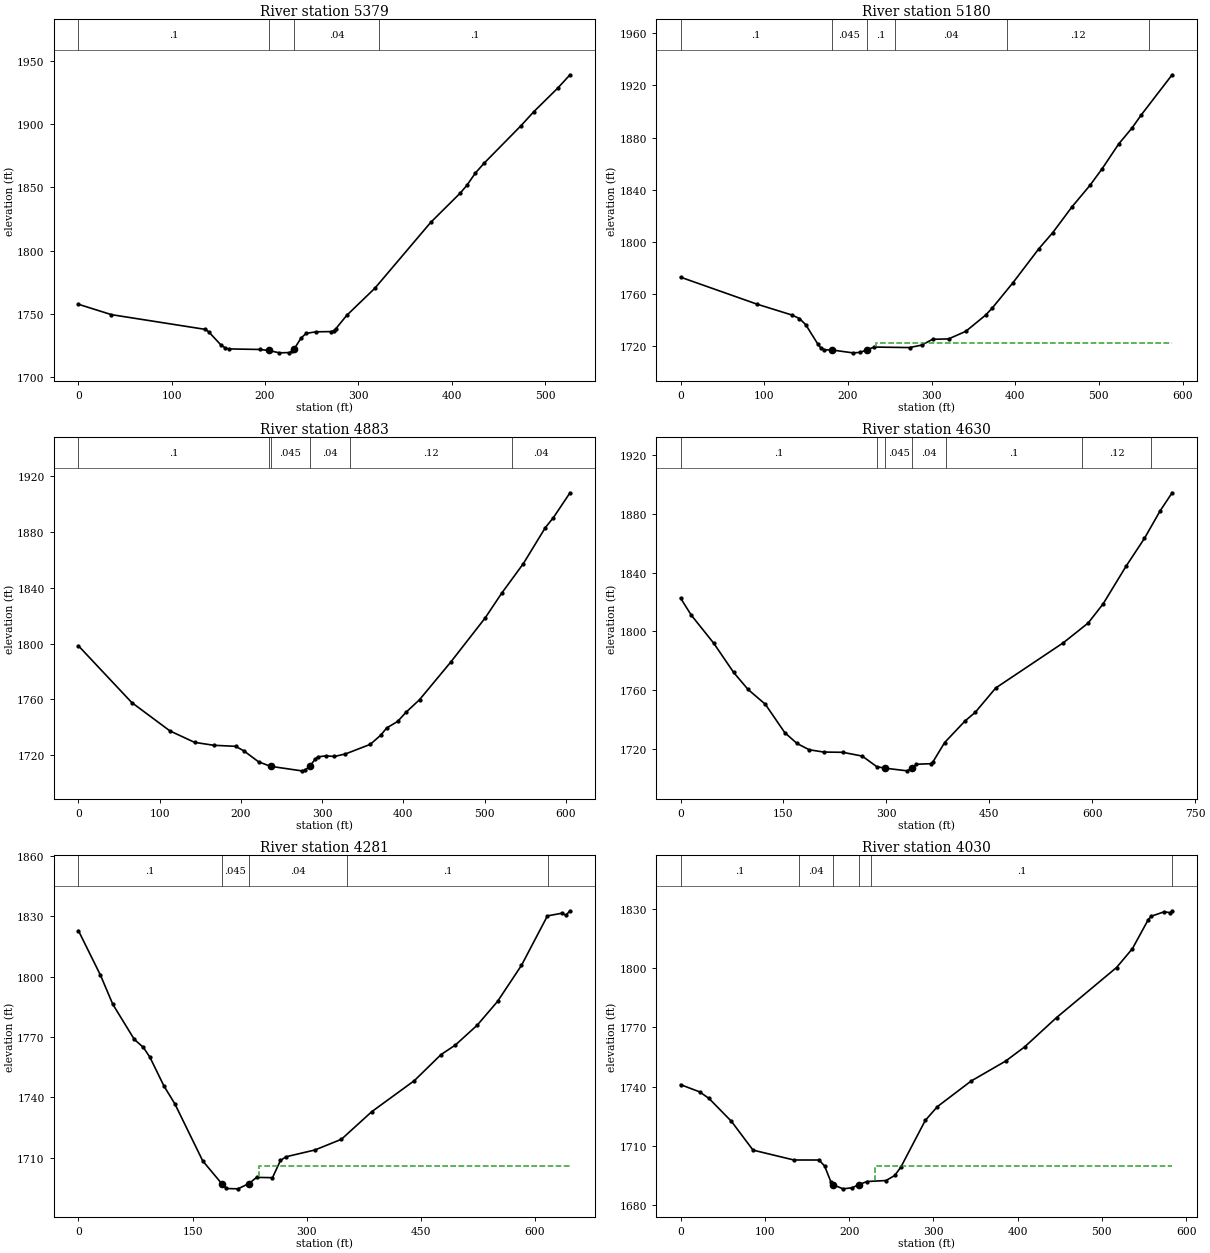
Type RM Length L Ch R = 1 ,5379    ,207.5,199,189
XS GIS Cut Line= 4
1970594.90627234217392.9547205061970668.56641953217321.791527459
1970840.85625533217243.1374719851971013.14609113217083.332406897
#Sta/Elev= 30
       0 1757.36    35.4 1749.12     136 1737.43   139.6 1735.52   152.6 1725.14
   157.6 1722.62   161.2 1721.94   194.1 1721.51     204 1720.71   215.3 1718.83
   226.1 1719.05   228.8 1719.91   231.11721.794   238.7 1730.69   244.2 1734.33
     255 1735.52   270.9 1735.68   273.4 1736.29   275.9 1737.99   287.4 1748.47
   317.7 1770.09   377.5  1822.3   409.2 1845.59   416.2 1851.64   425.4 1861.45
   434.7 1869.23   474.2 1898.96   488.1  1910.2   513.7 1928.88   526.8 1939.41
#Mann= 4 ,-1 , 0
       0      .1       0     204    .045       0   231.1     .04       0
  321.82      .1       0
Bank Sta=204,231.1
XS Rating Curve= 0 ,0
Exp/Cntr(USF)=0,0
Exp/Cntr=0.3,0.1

Type RM Length L Ch R = 1 ,5180    ,313,297,276.1
XS GIS Cut Line= 4
1970663.57251125217592.7110518671970762.20219986217514.056996393
1970943.23137515217365.4882249441971071.82451347217178.216664293
#Sta/Elev= 30
       0 1772.65    91.6 1751.85   133.1 1743.55   142.1 1740.86   149.7 1736.03
   164.1  1721.2   167.6 1718.31   171.8 1716.81  181.05 1716.66   205.8 1714.47
   214.3 1714.76  222.29 1716.66   231.4 1718.91   273.7 1718.52   288.2 1720.42
   301.2 1724.87   320.4 1725.19   340.9    1731   364.6 1743.46   372.5 1748.89
   397.3 1768.39   428.2 1794.49   444.9 1806.93     468 1826.85   489.3 1843.22
   503.8 1855.96   523.7  1875.1   539.7 1887.43   550.6 1897.37   587.5 1928.24
#Mann= 6 ,-1 , 0
       0      .1       0  181.05    .045       0  222.29      .1       0
  256.15     .04       0  390.34     .12       0  560.34     .04       0
#XS Ineff= 2 , 0
                          233.29         1721.75
Permanent Ineff=
       F       F
Bank Sta=181.05,222.29
XS Rating Curve= 0 ,0
Exp/Cntr(USF)=0,0
Exp/Cntr=0.3,0.1

Type RM Length L Ch R = 1 ,4883    ,248.9,252.3,253.7
XS GIS Cut Line= 4
1970993.17045799217809.9460622211971033.12172427217630.165363997
1971081.81233004217436.6514179911971130.50293581217220.664884707
#Sta/Elev= 30
       0 1798.46    65.6 1757.82   112.7 1737.45   142.9 1729.29   166.5 1727.18
   193.4 1726.44   203.6  1723.2   221.8 1715.31  236.491712.114   274.6 1708.87
   278.6 1709.16  284.771712.111   291.5 1717.35   294.9 1718.86   304.2 1719.61
   315.2 1719.17   328.7 1720.98   359.2 1727.84     372 1734.35   379.5 1739.63
     393 1744.29     403 1750.71   419.9 1759.88   458.1 1786.66   500.6 1818.38
   520.8    1836   547.7  1857.4   574.6 1883.05   584.7 1890.37   605.1 1908.12
#Mann= 6 ,-1 , 0
       0      .1       0  234.17     .04       0  236.49    .045       0
  284.77     .04       0  334.17     .12       0  533.71     .04       0
Bank Sta=236.49,284.77
XS Rating Curve= 0 ,0
Exp/Cntr(USF)=0,0
Exp/Cntr=0.3,0.1

Type RM Length L Ch R = 1 ,4630    ,315.9,349.7,350.6
XS GIS Cut Line= 4
1971166.70877086217948.5270171031971257.84759705217730.043529677
1971316.52601939217540.2750148841971327.76231302217259.367673908
#Sta/Elev= 30
       0 1822.71    15.6 1811.11    48.3 1792.04    77.4 1772.15    98.4 1760.56
   123.6  1750.5     152 1731.16   169.8 1723.84   187.6 1719.57   208.8 1718.01
   236.4 1717.85   264.8 1715.28   286.2 1708.04  297.521707.113   330.1 1705.25
  337.991707.115   343.9 1709.73   364.4 1710.11   367.8 1711.28     385 1724.51
   414.7 1739.16   429.6 1745.04   459.4 1761.57   557.9  1792.3   594.1 1805.71
   615.8 1818.64   649.2 1844.21   676.2  1863.3   699.1 1882.03   716.5 1894.26
#Mann= 7 ,-1 , 0
       0      .1       0  286.73     .04       0  297.52    .045       0
  337.99     .04       0  386.73      .1       0  585.36     .12       0
  685.36     .04       0
Bank Sta=297.52,337.99
XS Rating Curve= 0 ,0
Exp/Cntr(USF)=0,0
Exp/Cntr=0.3,0.1

Type RM Length L Ch R = 1 ,4281    ,258.4,250.8,236.5
XS GIS Cut Line= 4
1971309.03515696218064.6353847061971381.44682708217964.757219026
1971568.71838773217793.7158602981971807.17750829217668.868153198
#Sta/Elev= 30
       0 1822.84      29  1800.7    45.2 1786.25    73.4 1768.86    85.2 1764.93
    93.8  1760.1   112.3 1745.78   126.8 1736.79   163.4 1708.49  188.351697.211
   194.5 1694.79   209.6 1694.62  224.071697.212   234.2 1700.31   255.1 1700.16
   265.6 1708.71   272.8 1710.54   310.9 1713.92   345.7 1719.23   385.5 1732.91
   441.5 1748.33   476.7 1761.31   495.3 1765.97   524.1 1775.85   550.9 1787.68
   582.4 1805.61   616.5 1830.16   635.7 1831.51   640.8  1830.5   646.2 1832.71
#Mann= 5 ,-1 , 0
       0      .1       0  188.35    .045       0  224.07     .04       0
  353.37      .1       0  616.99     .04       0
#XS Ineff= 2 , 0
                          237.68         1705.78
Permanent Ineff=
       F       F
Bank Sta=188.35,224.07
XS Rating Curve= 0 ,0
Exp/Cntr(USF)=0,0
Exp/Cntr=0.3,0.1

Type RM Length L Ch R = 1 ,4030    ,187.3,204.7,214
XS GIS Cut Line= 4
1971546.24580045218201.9678625171971616.16051643218073.374724203
1971702.30543433217887.3516406241971815.91684779217685.098355121
#Sta/Elev= 30
       0 1741.05    22.5 1737.42    33.7 1734.11    60.4  1722.5      86 1707.97
   134.5 1702.98   164.4 1702.97     171 1699.91   178.3 1692.06  180.65 1690.59
   192.7 1688.41   203.6 1688.95  212.061690.589   221.2 1692.11   243.8  1692.6
   254.2 1695.16   261.4 1699.35   290.4 1722.95   304.8 1729.94   344.8 1742.86
   385.7 1752.92   408.3  1760.1   446.2 1774.92   517.4 1800.21   536.2 1809.71
     555 1824.37   558.8 1826.15   573.9 1828.35   581.1 1827.93   583.3 1828.87
#Mann= 6 ,-1 , 0
       0      .1       0     140     .04       0  180.65    .045       0
  212.06     .04       0  226.37      .1       0  583.35     .04       0
#XS Ineff= 2 , 0
                          231.23         1699.78
Permanent Ineff=
       F       F
Bank Sta=180.65,212.06
XS Rating Curve= 0 ,0
Exp/Cntr(USF)=0,0
Exp/Cntr=0.3,0.1

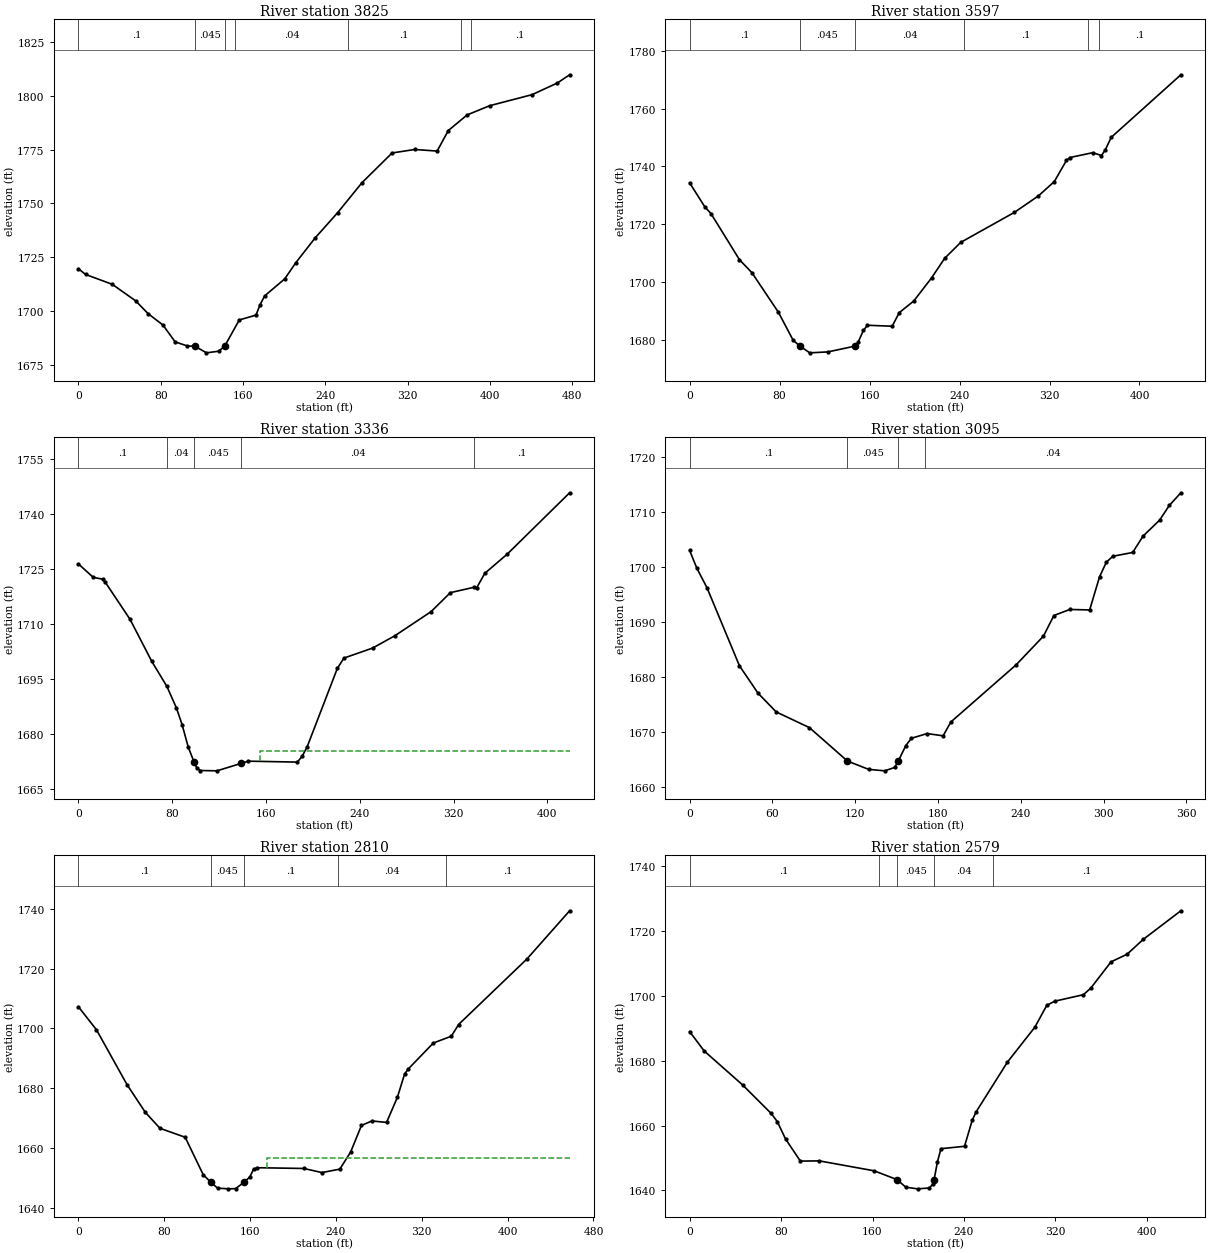
Type RM Length L Ch R = 1 ,3825    ,224.6,228,233.6
XS GIS Cut Line= 4
1971628.64528714218271.8825784931971671.09350755218240.670651718
1971775.96558151218165.7620274581972041.89119764218035.920412073
#Sta/Elev= 30
       0 1719.65       7 1717.01    32.9 1712.43    55.6 1704.77    67.7 1698.82
    82.2 1693.51      94 1685.72   105.7 1683.83  113.43 1683.63   124.5 1680.61
   136.3 1681.37  142.07 1683.63   156.4 1695.89   172.6 1698.14   176.6 1702.98
     181 1707.04   200.6 1714.98   211.3 1722.46     230 1733.91   252.1 1745.76
   275.6  1759.6   304.9 1773.42   326.8 1775.05   348.7 1774.31   359.6 1783.86
   377.9 1791.11   399.8 1795.38     441 1800.51   465.6 1805.93   477.5 1809.74
#Mann= 7 ,-1 , 0
       0      .1       0  113.43    .045       0  142.07      .1       0
  152.69     .04       0  261.57      .1       0  371.57     .04       0
  381.57      .1       0
Bank Sta=113.43,142.07
XS Rating Curve= 0 ,0
Exp/Cntr(USF)=0,0
Exp/Cntr=0.3,0.1

Type RM Length L Ch R = 1 ,3597    ,265.9,260.7,251.4
XS GIS Cut Line= 4
 1971733.5173611 218454.160230861971774.71710444218430.439166511
 1971897.0678574218369.2637900311972110.55743654218234.428266363
#Sta/Elev= 30
       0 1734.29    13.4 1726.04      19 1723.63    44.3  1707.7    55.4 1703.19
    78.9 1689.54    92.1 1679.79   98.151677.785   106.8 1675.47   122.9 1675.79
  146.851677.785   149.8 1679.12   154.5 1683.22   158.1 1685.01   180.1 1684.68
   186.4 1689.38   199.3 1693.41   215.1 1701.38   226.8 1708.19   241.1  1713.7
   288.7 1724.05   310.1 1729.76   324.3 1734.74   335.1 1742.07     338 1743.04
   358.4 1744.72   366.2 1743.75   369.5 1745.61   374.9 1750.04   436.8 1771.68
#Mann= 6 ,-1 , 0
       0      .1       0   98.15    .045       0  146.85     .04       0
  244.33      .1       0  354.33     .04       0  364.33      .1       0
Bank Sta=98.15,146.85
XS Rating Curve= 0 ,0
Exp/Cntr(USF)=0,0
Exp/Cntr=0.3,0.1

Type RM Length L Ch R = 1 ,3336    ,233.7,241.7,240.9
XS GIS Cut Line= 4
1971883.33460962 218690.122397281971934.52216953218650.171131007
1972073.10312441218534.0627634041972201.69626273218417.954395801
#Sta/Elev= 30
       0 1726.44    12.7 1722.77    20.7 1722.28      23 1721.41    44.1 1711.29
    62.6 1699.83    75.4 1693.06    83.5 1687.22    88.4 1682.62    93.7 1676.44
   98.671672.366   101.1 1670.66   103.9 1670.07   118.2 1669.98   139.1 1672.05
   144.8 1672.62  186.681672.365   190.8  1673.9   195.2 1676.61   220.9 1697.97
   226.5 1700.75     251 1703.49     270 1706.86   300.8 1713.42   317.3 1718.61
   337.3 1720.06   339.7 1719.92   346.6 1723.86     366 1729.19     419 1745.86
#Mann= 5 ,-1 , 0
       0      .1       0    75.4     .04       0   98.67    .045       0
   139.1     .04       0   337.3      .1       0
#XS Ineff= 2 , 0
       0                     155       0 1675.43
Permanent Ineff=
       F       F
Bank Sta=98.67,139.1
XS Rating Curve= 0 ,0
Exp/Cntr(USF)=0,0
Exp/Cntr=0.3,0.1

Type RM Length L Ch R = 1 ,3095    ,274.2,284.4,295
XS GIS Cut Line= 4
1971996.94602308218856.1698477231972059.36987663218823.709443877
1972186.71453788218745.0553884041972304.07138255218676.389149499
#Sta/Elev= 30
       0 1702.97     5.2 1699.75    12.6 1696.18    36.1 1682.02    49.6 1677.03
    62.8 1673.63    86.8 1670.79   114.41664.711   129.7 1663.21   141.3 1662.94
   148.6 1663.56   151.2 1664.71   156.7 1667.54   160.7 1668.85   172.1 1669.71
   183.7  1669.3   189.3 1671.81   236.6 1682.19   256.4  1687.4     264 1691.15
   275.5 1692.25   289.9 1692.16   297.1  1698.2     302 1700.83   306.7 1701.91
   321.1  1702.6   328.6 1705.57   340.6 1708.47   347.6 1711.13     356 1713.44
#Mann= 4 ,-1 , 0
       0      .1       0   114.4    .045       0   151.2      .1       0
  170.36     .04       0
Bank Sta=114.4,151.2
XS Rating Curve= 0 ,0
Exp/Cntr(USF)=0,0
Exp/Cntr=0.3,0.1

Type RM Length L Ch R = 1 ,2810    ,233,231.8,230.1
XS GIS Cut Line= 4
1972006.93383965219092.1320141431972080.59398684219072.156381007
 1972194.2054003219048.4353166581972453.88863107218993.502325534
#Sta/Elev= 30
       0 1707.25    16.8 1699.56    45.4 1681.15    62.4 1671.93      76 1666.62
    99.5 1663.62   116.3 1651.12  123.531648.528   129.7 1646.62   139.7 1646.38
   146.4 1646.45  154.241648.528   159.8 1650.37   163.2 1652.95   166.5 1653.44
   210.1 1653.19   226.9 1651.82   243.6 1652.96   253.7 1658.68   263.8 1667.58
   273.5 1669.07   287.2 1668.59   297.3 1677.01     304 1684.77   307.4 1686.45
   330.8 1695.13   347.6 1697.41   354.3 1701.31     418 1723.22   457.8 1739.33
#Mann= 5 ,-1 , 0
       0      .1       0  123.53    .045       0  154.24      .1       0
  242.38     .04       0  342.38      .1       0
#XS Ineff= 2 , 0
                          176.22         1656.78
Permanent Ineff=
       F       F
Bank Sta=123.53,154.24
XS Rating Curve= 0 ,0
Exp/Cntr(USF)=0,0
Exp/Cntr=0.3,0.1

Type RM Length L Ch R = 1 ,2579    ,275.5,277.5,278.5
XS GIS Cut Line= 4
1972084.33941805219284.3974830781972196.70235444219258.179464587
1972380.22848388219203.2464734621972495.08837441219159.549775977
#Sta/Elev= 30
       0 1688.99    12.7 1683.03    46.4 1672.53    71.4 1663.74    76.7 1661.24
    83.9  1655.9    96.9 1649.06   113.5 1649.13   161.4 1646.07  181.451643.359
   189.1 1641.03   199.4 1640.51   209.7 1640.77   213.1 1642.08  213.911643.354
   216.8 1648.81   219.9 1652.89   240.5 1653.62   247.3  1661.7   250.7 1664.27
   278.1  1679.6   302.1 1690.37   312.5 1697.09   319.5 1698.37   344.6 1700.37
   351.1 1702.44   368.7 1710.49   382.8 1712.85   396.8  1717.4   429.8 1726.24
#Mann= 5 ,-1 , 0
       0      .1       0  165.38     .04       0  181.45    .045       0
  213.91     .04       0  265.38      .1       0
Bank Sta=181.45,213.91
XS Rating Curve= 0 ,0
Exp/Cntr(USF)=0,0
Exp/Cntr=0.3,0.1

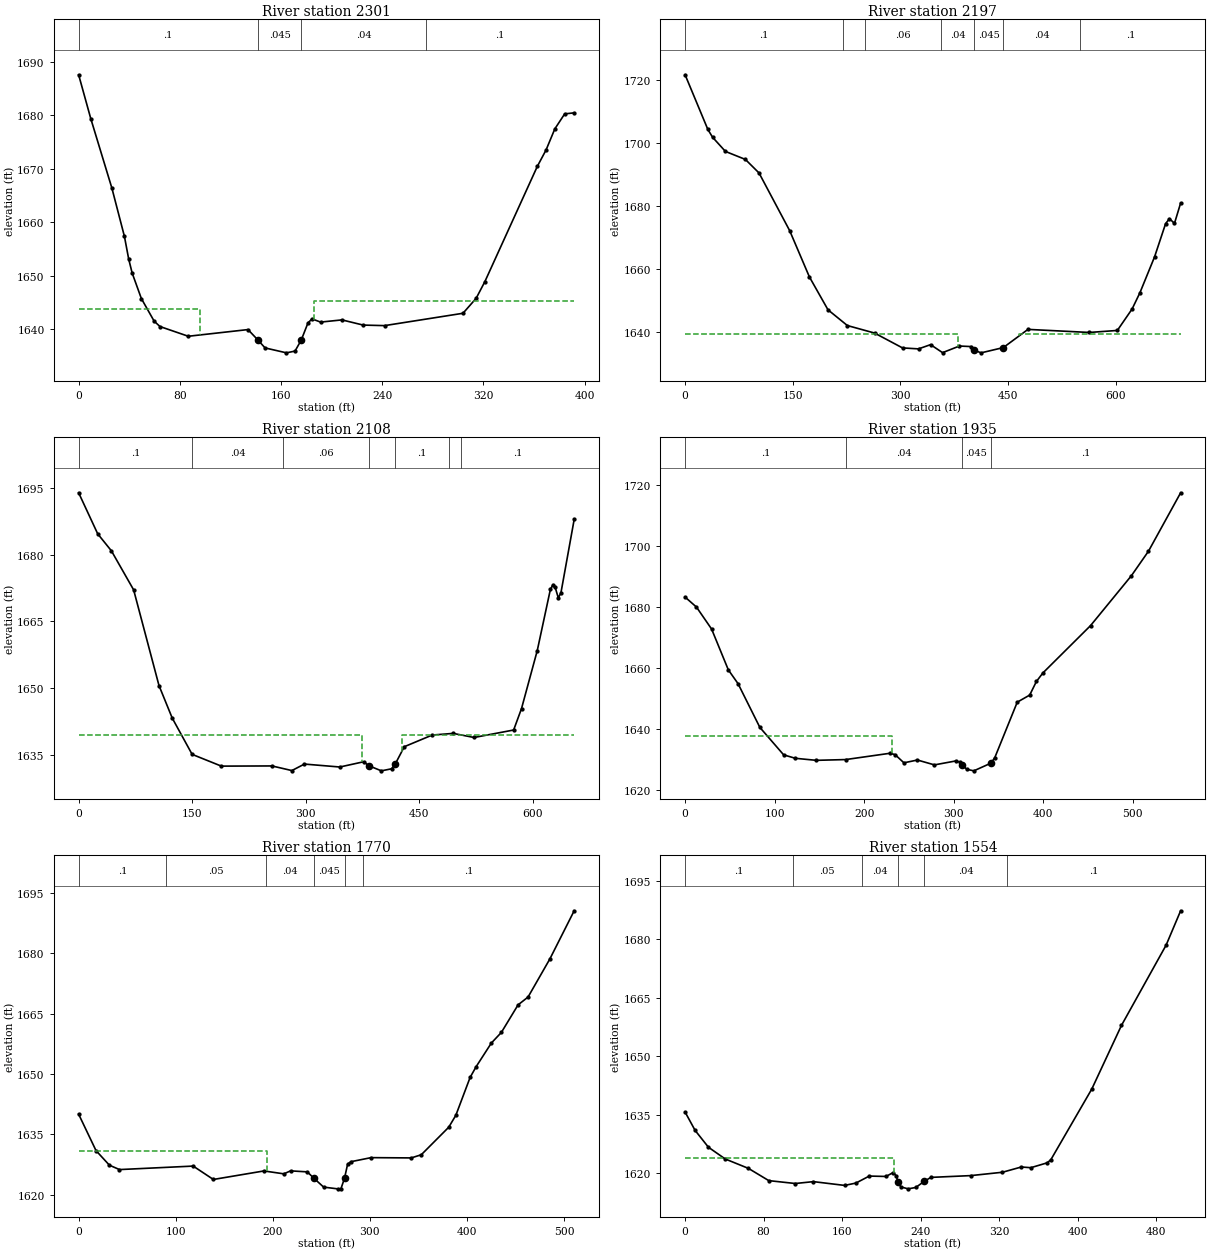
Type RM Length L Ch R = 1 ,2301    ,137,103.7,43.1
XS GIS Cut Line= 4
1972169.23585888219540.3352826341972214.18103344219532.844420208
1972417.68279601219484.153814438 1972547.5244114219440.457116953
#Sta/Elev= 30
       0 1687.56     9.6 1679.36    26.3 1666.36    36.2 1657.34    39.6 1653.08
    42.3  1650.5    49.6 1645.71    59.7 1641.49    64.3 1640.48    86.7 1638.66
   133.9 1639.91  141.741637.966   147.4 1636.48   164.3 1635.56   171.1 1635.89
  176.051637.967   181.3 1641.14   184.5 1641.91   191.3 1641.31   208.2 1641.72
     225 1640.75   241.9 1640.65   303.9 1642.96   314.3 1645.76   321.2 1648.88
   362.7 1670.45   369.6 1673.51   376.5 1677.44   384.3 1680.25   391.8 1680.44
#Mann= 4 ,-1 , 0
       0      .1       0  141.74    .045       0  176.05     .04       0
  274.81      .1       0
#XS Ineff= 2 , 0
           95.95 1643.68  186.25         1645.23
Permanent Ineff=
       F       F
Bank Sta=141.74,176.05
XS Rating Curve= 0 ,0
Exp/Cntr(USF)=0,0
Exp/Cntr=0.5,0.3

Type RM Length L Ch R = 1 ,2197    ,91.5,89.1,106.4
XS GIS Cut Line= 4
1972216.67798758219957.3266243491972391.46477752219692.649485296
1972359.00437367219542.8322367761972567.50004453219472.917520799
#Sta/Elev= 30
       0  1721.8    31.7 1704.39    38.3  1701.9    56.2 1697.39      84 1694.84
     103 1690.53   145.7 1672.16   173.2 1657.42   199.1 1646.95   226.1 1641.94
     264 1639.55   302.9 1634.82   325.2 1634.51     342 1635.86   358.7 1633.31
   382.2 1635.42     399 1635.24   402.4 1634.11   412.4 1633.25  443.361634.924
   477.7 1640.72   563.2 1639.74   602.2 1640.38   622.8 1647.22   633.7  1652.4
   654.1 1663.83   669.4 1674.36   674.8    1676   681.8 1674.46   690.4 1680.95
#Mann= 7 ,-1 , 0
       0      .1       0     220     .04       0     250     .06       0
  357.18     .04       0   402.4    .045       0  443.36     .04       0
  550.48      .1       0
#XS Ineff= 2 , 0
             380 1639.36     465         1639.36
Permanent Ineff=
       F       F
Bank Sta=402.4,443.36
XS Rating Curve= 0 ,0
Exp/Cntr(USF)=0,0
Exp/Cntr=0.5,0.3

Type RM Length L Ch R = 1 ,2108    ,140.9,173.3,204.4
XS GIS Cut Line= 4
1972269.11402456219964.8174867751972467.62187885219715.122072574
1972431.41604379219542.8322367761972582.48176938219490.396199793
#Sta/Elev= 30
       0 1693.88    25.2 1684.66    43.3 1680.84    72.7 1672.07   106.2 1650.58
   123.7 1643.27     150 1635.12   188.6 1632.48   255.5 1632.52   281.8 1631.48
   298.4 1632.94   345.2 1632.28   376.7 1633.46   383.6 1632.56   400.1 1631.42
   413.6 1631.88  418.571633.001   430.4 1636.84   467.3 1639.46     495 1639.83
   522.6 1638.91   574.9 1640.59   585.3  1645.4   606.1 1658.42   623.5 1672.21
     627 1673.26   629.5 1672.81   633.9 1670.29   637.4 1671.39   654.9 1687.88
#Mann= 7 ,-1 , 0
       0      .1       0     150     .04       0     270     .06       0
   383.6    .045       0  418.57      .1       0  488.99     .04       0
  505.04      .1       0
#XS Ineff= 2 , 0
             374 1639.36     427         1639.36
Permanent Ineff=
       F       F
Bank Sta=383.6,418.57
XS Rating Curve= 0 ,0
Exp/Cntr(USF)=0,0
Exp/Cntr=0.5,0.3

Type RM Length L Ch R = 1 ,1935    ,157.3,164.9,170.5
XS GIS Cut Line= 4
1972299.07747427219977.302257485  1972452.640154 219821.24262361
1972589.97263181219732.6007515681972738.54140326 219647.70431074
#Sta/Elev= 30
       0 1683.13    12.7 1679.86    29.6 1672.67    48.3 1659.29    59.1  1654.8
    83.5 1640.46   110.1 1631.46   123.1 1630.34   146.5 1629.67   179.3 1629.92
   228.8 1631.98   234.5 1631.55   244.4 1628.86   259.5 1629.77   278.5 1628.18
   302.2 1629.46     307 1629.11   309.3 1628.21   314.7 1626.73   322.5 1626.23
  341.661628.754   345.9 1630.54     371 1648.72   384.9 1651.04   392.4  1655.5
   399.7  1658.3   452.9  1673.8   498.5 1690.13   517.6 1698.17   553.5 1717.29
#Mann= 4 ,-1 , 0
       0      .1       0     180     .04       0   309.3    .045       0
  341.66      .1       0
#XS Ineff= 2 , 0
          230.58 1637.52
Permanent Ineff=
       F       F
Bank Sta=309.3,341.66
XS Rating Curve= 0 ,0
Exp/Cntr(USF)=0,0
Exp/Cntr=0.3,0.1

Type RM Length L Ch R = 1 ,1770    ,220,215.8,210.2
XS GIS Cut Line= 4
1972355.25894246219997.277890621 1972443.9008145219968.562917988
1972668.62668728219893.6542937281972840.91652308219839.969779675
#Sta/Elev= 30
       0 1639.99    17.9 1630.93    31.7  1627.3    42.1 1626.21     118 1627.08
   138.8 1623.75   190.9 1625.87   211.4 1625.15   218.3 1625.89   235.6 1625.64
   242.1 1624.11   252.4 1621.85   266.7 1621.42   270.2 1621.42   273.91624.053
   277.1 1627.55   280.5 1628.17   301.3 1629.18   342.7 1629.11     353  1629.9
   381.3 1636.75   388.6 1639.71   403.3 1649.13   409.5  1651.8   425.2 1657.68
   435.5 1660.32   452.7 1667.17     463 1669.12   485.5 1678.61   510.5 1690.57
#Mann= 6 ,-1 , 0
       0      .1       0      90     .05       0  193.18     .04       0
   242.1    .045       0   273.9     .04       0  293.18      .1       0
#XS Ineff= 2 , 0
          194.27 1630.95
Permanent Ineff=
       F       F
Bank Sta=242.1,273.9
XS Rating Curve= 0 ,0
Exp/Cntr(USF)=0,0
Exp/Cntr=0.3,0.1

Type RM Length L Ch R = 1 ,1554    ,116.5,120.8,129.2
XS GIS Cut Line= 4
1972431.41604379 220194.537267841972631.17237515220137.107322574
1972746.03226569220067.1926065981972887.11017471219986.041596982
#Sta/Elev= 30
       0 1635.68    10.2 1630.97    23.8 1626.64    40.9 1623.63    64.5 1621.22
    85.3 1618.07   112.3 1617.33   130.8 1617.81   162.6 1616.84   174.1 1617.44
   187.7 1619.24   204.8 1619.14   212.1 1620.15   214.9 1619.38   217.3 1617.73
   219.8 1616.46   227.4 1615.96   235.1 1616.31  243.951617.921   250.5  1618.9
   291.3 1619.36   323.5 1620.22   342.7 1621.57   352.4 1621.39   369.2 1622.65
   372.9 1623.48   414.6 1641.62   444.8 1657.94   490.3 1678.55   505.1 1687.37
#Mann= 6 ,-1 , 0
       0      .1       0     110     .05       0     180     .04       0
   217.3    .045       0  243.95     .04       0  327.85      .1       0
#XS Ineff= 2 , 0
          213.19 1623.81
Permanent Ineff=
       F       F
Bank Sta=217.3,243.95
XS Rating Curve= 0 ,0
Exp/Cntr(USF)=0,0
Exp/Cntr=0.3,0.1

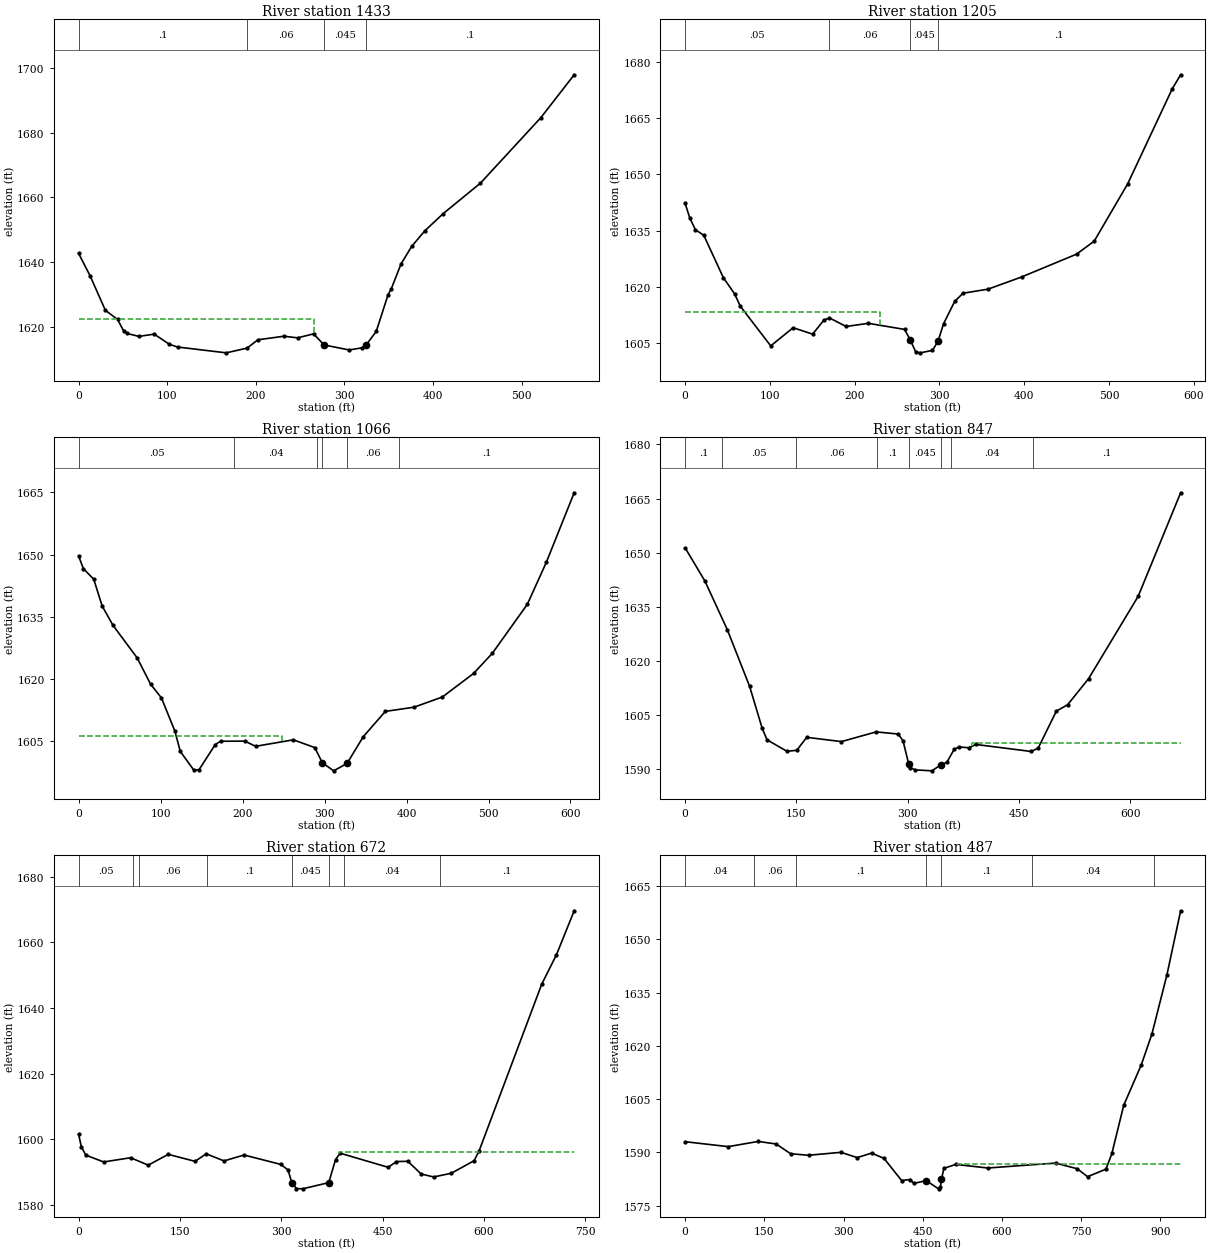
Type RM Length L Ch R = 1 ,1433    ,215.8,228.5,246
XS GIS Cut Line= 4
1972455.13710814220301.906295947 1972693.5962287220225.749194615
1972828.43175237220159.5799098521972965.76423018220079.677377308
#Sta/Elev= 30
       0 1642.73    12.9 1635.84    30.2 1625.18    43.9 1622.38    50.8 1618.83
    54.3 1618.06      68 1617.14    85.3 1617.83   102.5 1614.68   111.8 1613.85
   166.6 1612.06   190.1 1613.51   202.4 1616.09   231.9 1617.19   247.1 1616.68
   265.2 1617.92   277.1 1614.49   305.4 1612.95     320 1613.61  324.72 1614.55
     336 1618.69   349.3 1629.99   352.9 1631.77   363.9 1639.46   375.9 1644.88
   390.8 1649.71   411.7 1655.05   453.6 1664.42   521.9 1684.66   559.4 1697.85
#Mann= 4 ,-1 , 0
       0      .1       0     190     .06       0   277.1    .045       0
  324.72      .1       0
#XS Ineff= 2 , 0
          265.37 1622.64
Permanent Ineff=
       F       F
Bank Sta=277.1,324.72
XS Rating Curve= 0 ,0
Exp/Cntr(USF)=0,0
Exp/Cntr=0.3,0.1

Type RM Length L Ch R = 1 ,1205    ,139.7,139,138.9
XS GIS Cut Line= 4
1972465.12492471220447.9781132541972682.35993506220431.747911331
 1972818.4439358220431.7479113311973048.16371687220450.475067396
#Sta/Elev= 30
       0 1642.24     5.6 1638.28    12.2 1635.21    22.1 1633.71    45.1 1622.44
    58.3 1618.16    65.2 1614.81     101 1604.27   127.4 1609.11   150.4  1607.4
   163.5 1611.08   170.1 1611.73   189.9 1609.44   216.2 1610.28   258.8 1608.66
   265.4 1605.93     272 1602.65   277.4 1602.42   291.7 1603.08   298.2 1605.44
   304.8 1610.16   317.9  1616.1   327.7 1618.29   357.3 1619.38   396.8 1622.62
   461.6  1628.7   482.4 1632.14   521.9  1647.4   574.5 1672.73   584.4 1676.47
#Mann= 4 ,-1 , 0
       0     .05       0   170.1     .06       0   265.4    .045       0
   298.2      .1       0
#XS Ineff= 2 , 0
          230.37 1613.24
Permanent Ineff=
       F       F
Bank Sta=265.4,298.2
XS Rating Curve= 0 ,0
Exp/Cntr(USF)=0,0
Exp/Cntr=0.3,0.1

Type RM Length L Ch R = 1 ,1066    ,216.2,218.6,215.7
XS GIS Cut Line= 4
1972442.01891745220581.7431991171972712.12585589220571.354470715
1972851.63163729220566.9021585431973046.04926881220557.997534199
#Sta/Elev= 30
       0 1649.69     5.8 1646.62    18.4 1644.11    28.7 1637.64    41.9 1632.99
    71.4 1625.14    87.8  1618.8     101 1615.51   117.4  1607.5     124 1602.62
   140.4 1598.13   146.9  1598.2   166.6 1604.25   173.2 1605.06   202.8 1605.09
   215.9 1603.84   261.9  1605.4   288.1 1603.53   297.21599.892   311.1 1597.93
   327.5 1599.73   347.2 1606.15   374.1 1612.25   409.1 1613.26   443.7 1615.72
   481.8 1621.39   504.8 1626.28   547.3 1638.03   570.5 1648.15   604.5 1664.92
#Mann= 6 ,-1 , 0
       0     .05       0     190     .04       0  290.31     .06       0
   297.2    .045       0   327.5     .06       0  390.31      .1       0
#XS Ineff= 2 , 0
          247.68 1606.29
Permanent Ineff=
       F       F
Bank Sta=297.2,327.5
XS Rating Curve= 0 ,0
Exp/Cntr(USF)=0,0
Exp/Cntr=0.3,0.1

Type RM Length L Ch R = 1 ,847     ,181.7,175.7,170.3
XS GIS Cut Line= 4
1972483.85208077220732.6308854431972737.29292619220782.569968283
1972887.11017471220777.5760599991973063.63641451220587.209828818
#Sta/Elev= 30
       01651.319  26.7631642.078  56.8581628.613  86.9531612.869 103.673 1601.37
 110.3611598.035 137.1121594.854 150.4881595.103 163.8631598.717 210.6781597.534
 257.4931600.221 287.0521599.634 293.617 1597.82   301.31591.373 303.4651590.309
 310.0311589.689 332.4641589.414   345.21591.138 352.7051591.755 362.5531595.361
 369.1181596.043 382.2491595.823 392.0971596.726 466.6131594.786 475.8991595.751
 500.3261605.988 515.3661607.732 543.7521614.986 610.5491637.836 667.8311666.597
#Mann= 8 ,-1 , 0
       0      .1       0      50     .05       0     150     .06       0
  258.31      .1       0   301.3    .045       0   345.2      .1       0
  358.31     .04       0  468.21      .1       0
#XS Ineff= 2 , 0
                          387.11         1597.13
Permanent Ineff=
       F       F
Bank Sta=301.3,345.2
XS Rating Curve= 0 ,0
Exp/Cntr(USF)=0,0
Exp/Cntr=0.3,0.1

Type RM Length L Ch R = 1 ,672     ,179.8,184.3,193.8
XS GIS Cut Line= 4
1972548.77288847220926.1448314491972809.70459631220954.859804082
1972985.73986332220907.417675384 1973124.3208182220653.899568692
#Sta/Elev= 30
       01601.468   4.0121597.655  10.6131595.133  37.0181593.052  76.9131594.337
 103.0311592.083 132.7371595.368 172.3451593.235 188.8481595.529 215.2531593.369
 244.9591595.168 299.4021592.296 310.1081590.597  315.631586.724 322.5931584.938
  331.521584.853  370.371586.748 380.357 1593.74 387.1531595.725 458.4361591.414
 470.6141593.171 487.537 1593.25 507.0431589.387 525.7381588.469 551.9111589.613
 585.5621593.428  593.041596.458 685.7731647.287 707.5311656.228 733.7451669.635
#Mann= 8 ,-1 , 0
       0     .05       0      80     .04       0      90     .06       0
     190      .1       0  315.63    .045       0  370.37      .1       0
  392.51     .04       0  534.82      .1       0
#XS Ineff= 2 , 0
                           386.1         1595.99
Permanent Ineff=
       F       F
Bank Sta=315.63,370.37
XS Rating Curve= 0 ,0
Exp/Cntr(USF)=0,0
Exp/Cntr=0.3,0.1

Type RM Length L Ch R = 1 ,487     ,176.7,170.8,159.8
XS GIS Cut Line= 4
1972511.31857634 220977.332391361972863.38911036221075.962079969
1973061.89696465221110.919437958 1973238.0237148220784.166696481
#Sta/Elev= 30
       01593.001  81.6581591.605 138.4381593.073 172.5091592.348 199.7661589.609
 233.8381589.182 295.1661590.007  325.831588.524 353.0881589.782 376.6861588.307
 409.9991582.058 425.9781582.343 433.3181581.253   456.61582.045 479.9571579.727
 483.2881580.117   485.51582.363  489.951585.492 512.5331586.601   573.21585.595
 701.5521586.982 742.7221585.377 762.0961583.147  797.031585.272 808.2111589.692
 830.5741603.237 863.8081614.617 883.9771623.295 912.2431639.853 938.3851658.009
#Mann= 7 ,-1 , 0
       0     .04       0     130     .06       0     210      .1       0
   456.6    .045       0   485.5      .1       0  657.19     .04       0
  887.19      .1       0
#XS Ineff= 2 , 0
                          514.33         1586.74
Permanent Ineff=
       F       F
Bank Sta=456.6,485.5
XS Rating Curve= 0 ,0
Exp/Cntr(USF)=0,0
Exp/Cntr=0.3,0.1

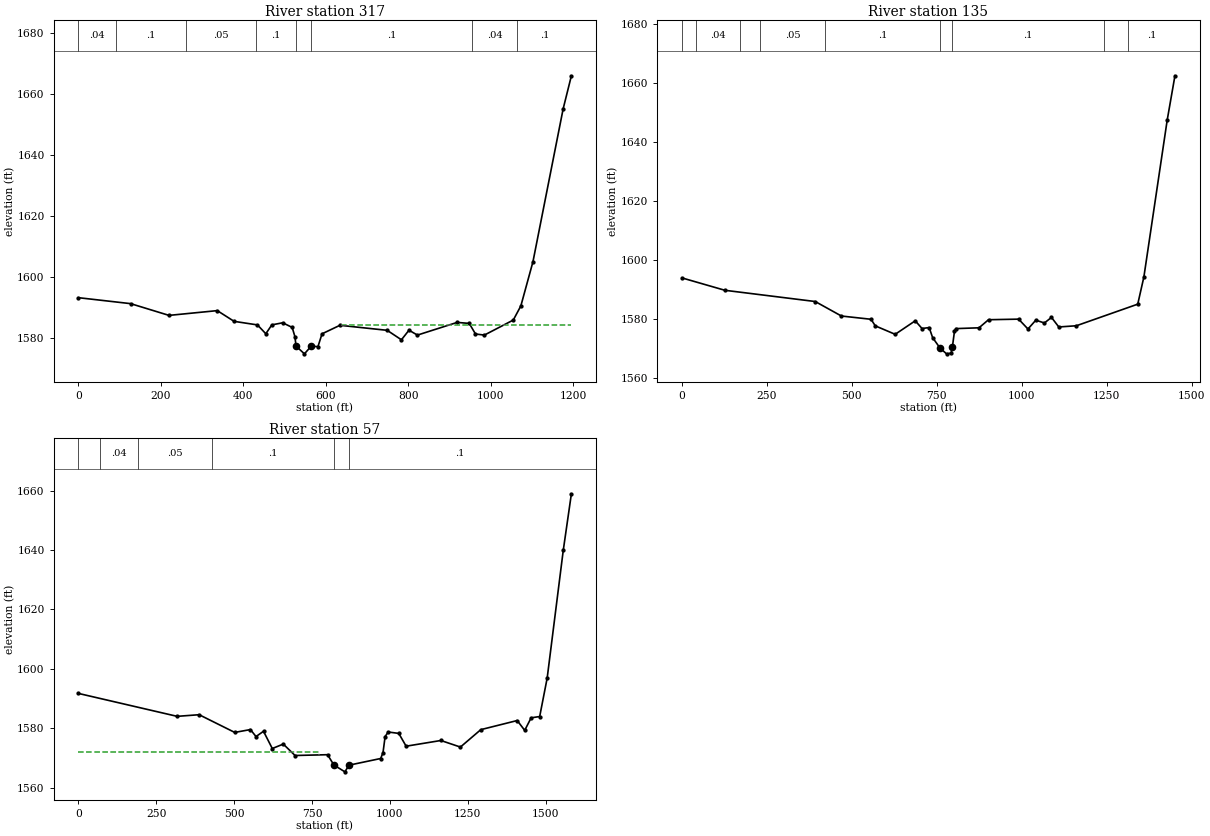
Type RM Length L Ch R = 1 ,317     ,180.9,181.2,170.8
XS GIS Cut Line= 4
1972460.13101643220983.5747767151972834.67413773221254.494301123
1973096.50880676221233.2648803161973307.01706384220812.034103877
#Sta/Elev= 30
       01593.314  126.471591.371   219.61587.531 336.6951589.089 377.5171585.582
 434.2051584.416 454.4511581.529 469.0781584.429  495.411585.113 518.4521583.594
 525.0351580.597  527.861577.479 548.0761574.961   564.51577.437 580.9921577.327
 590.8671581.507  634.291584.293 748.9131582.648 783.4821579.553 801.8211582.686
 822.3051581.091 918.6971585.235 948.0431584.911   963.21581.445 984.7271581.092
1054.8931586.0091073.2321590.6251102.5731605.0571175.9271655.0891195.8521665.863
#Mann= 8 ,-1 , 0
       0     .04       0      90      .1       0     260     .05       0
     430      .1       0  527.86    .045       0   564.5      .1       0
  954.95     .04       0 1064.95      .1       0
#XS Ineff= 2 , 0
                          637.82         1584.37
Permanent Ineff=
       F       F
Bank Sta=527.86,564.5
XS Rating Curve= 0 ,0
Exp/Cntr(USF)=0,0
Exp/Cntr=0.3,0.1

Type RM Length L Ch R = 1 ,135     ,62.2,78,91.7
XS GIS Cut Line= 4
 1972405.1980253220991.0656391411972930.80687219221406.808503786
 1973144.0001366221346.0567886791973378.72790538 220838.76452635
#Sta/Elev= 30
       0 1593.99 126.2021589.807 392.0161586.008 469.0931581.101 556.255    1580
 568.8041577.772 627.3671574.912 686.4311579.486 706.3321576.875 727.3691577.197
 737.6031573.781  759.441570.254  778.541568.306 792.1861568.522   795.71570.605
 801.9081575.962 805.8321576.842 874.0611577.116 902.0371579.847 990.6631580.049
1018.1951576.7061041.2731579.6981066.5781578.7461087.3961580.635 1108.951577.398
1160.5691577.806 1341.321585.1171359.395 1594.33 1428.081647.435  1450.8 1662.39
#Mann= 9 ,-1 , 0
       0     .05       0      40     .04       0     170      .1       0
     230     .05       0     420      .1       0  759.44    .045       0
   795.7      .1       0 1241.83     .04       0 1311.83      .1       0
Bank Sta=759.44,795.7
XS Rating Curve= 0 ,0
Exp/Cntr(USF)=0,0
Exp/Cntr=0.3,0.1

Type RM Length L Ch R = 1 ,57      ,89,89,89
XS GIS Cut Line= 5
1972379.49360482221037.2071026211972947.10711706221438.937540708
1973223.60673787 221432.720120321973256.87632634221295.095062053
1973398.18850344220847.593939142
#Sta/Elev= 30
       0 1591.71   316.8    1584   387.4 1584.55   501.7 1578.59   552.2 1579.55
     570  1577.2   594.1 1578.97   622.3 1573.17   657.6 1574.66   695.4 1570.82
   799.8 1571.09 820.1281567.615   855.5 1565.32 868.6751567.563   970.4 1569.81
   977.9 1571.81   984.6 1577.19   994.5 1578.73  1028.5 1578.26  1052.1 1573.95
  1163.7 1575.87  1226.4 1573.66  1291.9 1579.52  1408.8 1582.59  1432.9 1579.28
  1453.5  1583.5    1481 1583.94  1505.1 1596.92  1556.7 1639.88  1582.8 1658.92
#Mann= 6 ,-1 , 0
       0     .05       0      70     .04       0     190     .05       0
     430      .1       0 820.128    .045       0 868.675      .1       0
#XS Ineff= 2 , 0
          772.41  1572.1
Permanent Ineff=
       F       F
Bank Sta=820.128,868.675
XS Rating Curve= 0 ,0
Exp/Cntr(USF)=0,0
Exp/Cntr=0.3,0.1
LCMann Table=0

Chan Stop Cuts=-1
Use User Specified Reach Order=0
Composite Channel Slope=5